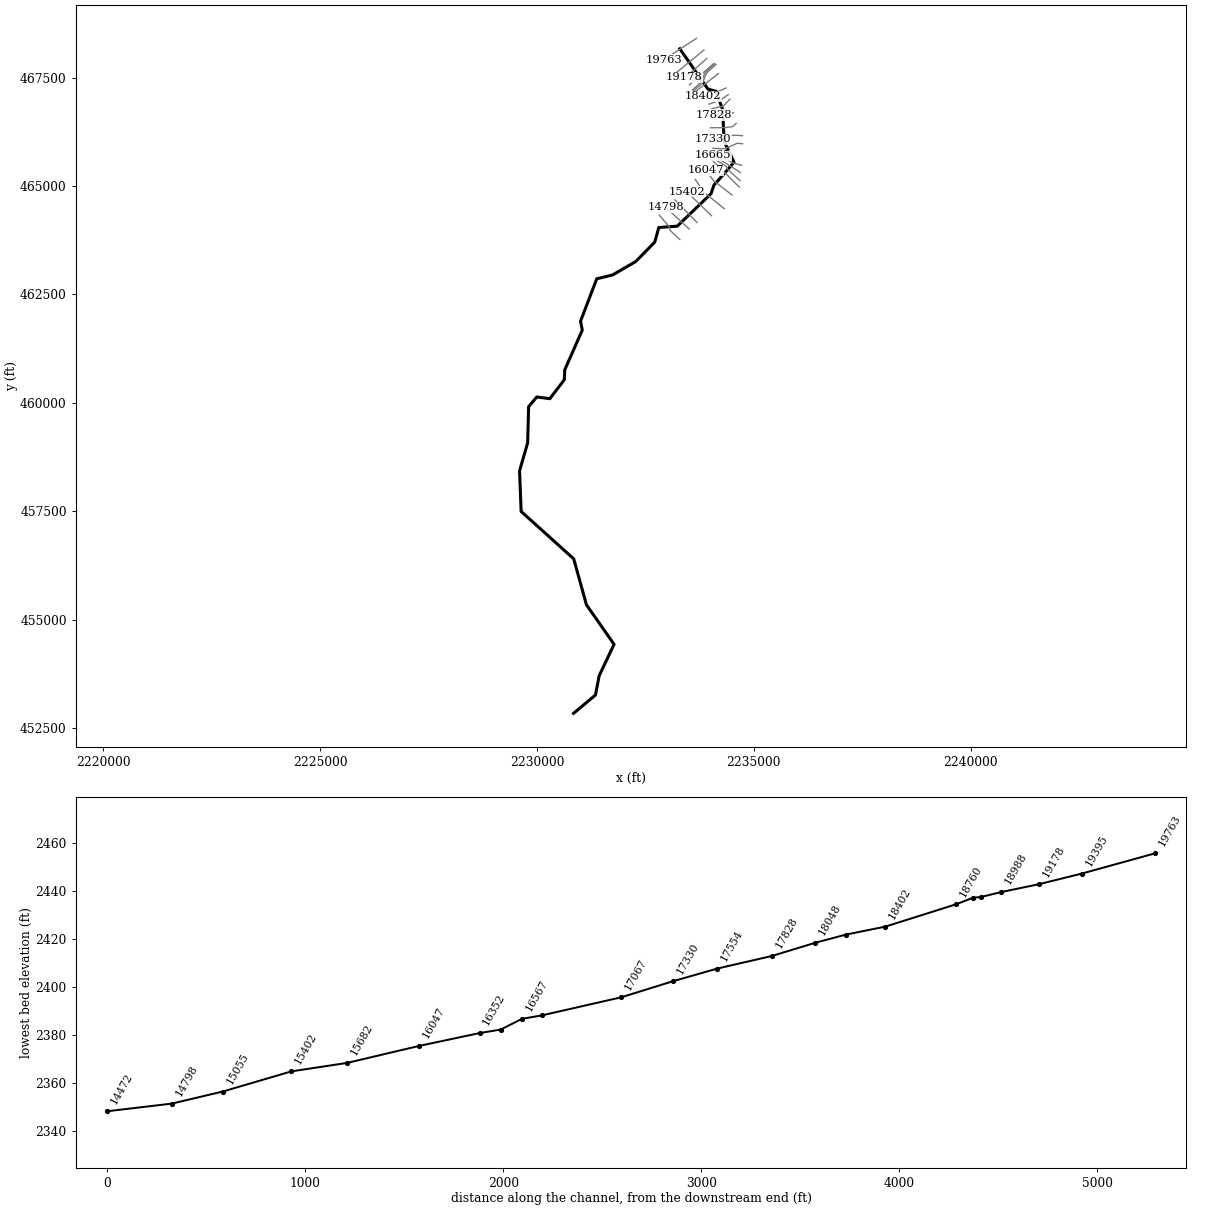
--- INDIANDRFT.prj (project) ---

Proj Title=INDIANDRFT
Current Plan=p01
Default Exp/Contr=0,0
English Units
Geom File=g01
Flow File=f01
Plan File=p01
Background Map Layer=Inundation Boundary (01pct Value_0)
BEGIN DESCRIPTION:
----------MODEL BY WOOD PLC 2021----------
Stream Name: Indian Draft
Flood Zone: Enhanced Approximate
Pocahontas County, WV
HEC-RAS Version: RAS 6.1
Vertical Datum: NAVD88
Projection: NAD 1983 StatePlane West Virginia S FIPS 4702 (US Feet)
Terrain: 1-meter LIDAR (FEMA Region III 3DEP collected 2016-2018)
Land Use: 2019 NLCD
Hydrologic Method:
WV SIR2010-5033 regression equations
Model Notes:
Normal depth tie in to Stony Creek
END DESCRIPTION:
DSS Export Rating Curves= 0
DSS Export Rating Curve Sorted= 0
DSS Export Volume Flow Curves= 0
DXF OffsetX= 0
DXF OffsetY= 0
DXF ScaleX= 0
DXF ScaleY= 0

--- INDIANDRFT.p01 (plan) ---

Plan Title=Floodplain
Program Version=6.10
Short Identifier=Floodplain
Geom File=g01
Flow File=f01
Subcritical Flow
K Sum by GR= 0
Std Step Tol= 0.01
Critical Tol= 0.01
Num of Std Step Trials= 20
Max Error Tol= 0.3
Flow Tol Ratio= 0.001
Split Flow NTrial= 30
Split Flow Tol= 0.02
Split Flow Ratio= 0.02
Log Output Level= 0
Friction Slope Method= 1
Unsteady Friction Slope Method= 2
Unsteady Bridges Friction Slope Method= 1
Parabolic Critical Depth
Global Vel Dist= 0 , 0 , 0
Global Log Level= 0
CheckData=False
Encroach Param=-1 ,0,0, 0
Mapping Interval=1HOUR
Computation Time Step Use Courant=        0
Computation Time Step Use Time Series=    0
Computation Time Step Count To Double=0
Computation Time Step Max Doubling=0
Computation Time Step Max Halving=0
Computation Time Step Residence Courant=0
Run HTab= 0
Run UNet= 0
Run Sediment= 0
Run PostProcess= 0
Run WQNet= 0
Run RASMapper=-1
UNET Theta= 0
UNET Theta Warmup= 0
UNET ZTol= 0
UNET ZSATol= 0
UNET MxIter= 0
UNET Max Iter WO Improvement= 0
UNET MaxInSteps= 0
UNET DtIC= 0
UNET DtMin= 0
UNET MaxCRTS= 0
UNET WFStab= 0
UNET SFStab= 0
UNET WFX= 1
UNET SFX= 1
UNET Gravity=32.174
UNET 1D Methodology=Finite Difference
UNET DSS MLevel= 1
UNET Pardiso=0
UNET DZMax Abort= 0
UNET Use Existing IB Tables= 0
UNET Froude Reduction=False
UNET Froude Limit= 0
UNET Froude Power= 0
UNET D1 Cores= 0
UNET WindReference=Eulerian
UNET WindDragFormulation=Hsu (1988)
UNET D2 Coriolis=0
UNET D2 Cores= 0
UNET D2 Theta= 1
UNET D2 Theta Warmup= 1
UNET D2 Z Tol= 0.01
UNET D2 Volume Tol= 0.01
UNET D2 Max Iterations= 20
UNET D2 Equation= 0
UNET D2 RampUpFraction=0.1
UNET D2 TimeSlices= 1
UNET D2 Turbulence Formulation=Non-Conservative (original)
UNET D2 Eddy Viscosity=0.3
UNET D2 Transverse Eddy Viscosity=0.1
UNET D2 Smagorinsky Mixing=0
UNET D2 BCVolumeCheck=0
UNET D2 Cores=0
UNET D2 SolverType=PARDISO (Direct)
UNET D2 Minimum Iterations= 2147483647
UNET D2 Maximum Iterations= 2147483647
UNET D2 Restart Number= 10
UNET D2 Relaxation Coeff=1.3
UNET D2 SOR Precondition Iterations= 10
UNET D2 ILUT Maximum Fill= 8
UNET D2 ILUT Tolerance=1E-08
UNET D1D2 MaxIter= 0
UNET D1D2 ZTol=0.01
UNET D1D2 QTol=0.1
UNET D1D2 MinQTol=1
Write IC File= 0
Write IC File at Fixed DateTime=0
Write IC File at Sim End=0
Echo Input=False
Echo Parameters=False
Echo Output=False
Write Detailed= 0
HDF Write Warmup=0
HDF Write Time Slices=0
HDF Flush=0
HDF Compression= 1
HDF Chunk Size= 1
HDF Spatial Parts= 1
HDF Use Max Rows=0
HDF Fixed Rows= 1
Calibration Method= 0
Calibration Iterations= 20
Calibration Max Change=0.05
Calibration Tolerance=0.2
Calibration Maximum=1.5
Calibration Minimum=0.5
Calibration Optimization Method= 1
WQ AD Non Conservative
WQ ULTIMATE=-1
WQ Max Comp Step=1HOUR
WQ Output Interval=15MIN
WQ Output Selected Increments= 0
WQ Output face flow=0
WQ Output face velocity=0
WQ Output face area=0
WQ Output face dispersion=0
WQ Output cell volume=0
WQ Output cell surface area=0
WQ Output cell continuity=0
WQ Output cumulative cell continuity=0
WQ Output face conc=0
WQ Output face dconc_dx=0
WQ Output face courant=0
WQ Output face peclet=0
WQ Output face adv mass=0
WQ Output face disp mass=0
WQ Output cell mass=0
WQ Output cell source sink temp=0
WQ Output nsm pathways=0
WQ Output nsm derived pathways=0
WQ Create Restart=0
WQ Fixed Restart=0
WQ System Summary=0
WQ Write To DSS=0
Sorting and Armoring Iterations= 10
XS Update Threshold= 0.02
Bed Roughness Predictor= 0
Hydraulics Update Threshold= 0.02
Energy Slope Method= 1
Volume Change Method= 1
Sediment Retention Method= 0
Sediment TS Multiplier= 1
Warm Up Method= 0
XS Weighting Method= 0
Number of US Weighted Cross Sections= 1
Number of DS Weighted Cross Sections= 1
Upstream XS Weight=0
Main XS Weight=1
Downstream XS Weight=0
Number of DS XS's Weighted with US Boundary= 1
Upstream Boundary Weight= 1
Weight of XSs Associated with US Boundary= 0
Number of US XS's Weighted with DS Boundary= 1
Downstream Boundary Weight= 0.5
Weight of XSs Associated with DS Boundary= 0.5
Percentile Method= 0
Sediment Output Level= 3
Mass or Volume Output= 0
Output Increment Type= 1
Profile and TS Output Increment= 1
Transport Output Increment 1
XS Output Flag= 0
XS Output Increment= 10
Read HDF5 Sediment Hotstart= 0
Sediment Hotstart Type= 0
Write Gradation File= 0
Read Gradation Hotstart= 0
Write HDF5 File= 1
Write Binary Output= 1
Write DSS Sediment File= 0
DSS Sediment Output Type= 1
SV Curve= 0
Specific Gage Flag= 0
Subcell Erosion Methods= 0
Subcell Deposition Methods= 0
Advection Scheme= 1
Matrix Solver= 0
Implicit Weighting Factor= 1
Maximum Outer Loop Convergence Iterations= 5
Convergence Maximum Absolute= 0.001
Convergence RMSE= 0.0001
Grain Fractions Max Abs Error= 0.001
Max Subgrid Regions= 1
Max Subgrid Length Scale= 3.402823E+38
Initial Layer Thickness= 3.402823E+38
Min Layer Thickness= 3.402823E+38
Max Layer Thickness= 3.402823E+38
Number of Layers= 5

--- INDIANDRFT.f01 (steady flow) ---

Flow Title=Flow
Program Version=6.10
Number of Profiles= 6
Profile Names=01pct,10pct,04pct,02pct,0_2pct,01plus
River Rch & RM=INDIANDRFT,Main,19763
     984     531     699     837    1360    1460
River Rch & RM=INDIANDRFT,Main,8378
    1500     820    1070    1280    2050    2210
Boundary for River Rch & Prof#=INDIANDRFT,Main            , 1
Up Type= 0
Dn Type= 3
Dn Slope=0.012463
Boundary for River Rch & Prof#=INDIANDRFT,Main            , 2
Up Type= 0
Dn Type= 3
Dn Slope=0.012463
Boundary for River Rch & Prof#=INDIANDRFT,Main            , 3
Up Type= 0
Dn Type= 3
Dn Slope=0.012463
Boundary for River Rch & Prof#=INDIANDRFT,Main            , 4
Up Type= 0
Dn Type= 3
Dn Slope=0.012463
Boundary for River Rch & Prof#=INDIANDRFT,Main            , 5
Up Type= 0
Dn Type= 3
Dn Slope=0.012463
Boundary for River Rch & Prof#=INDIANDRFT,Main            , 6
Up Type= 0
Dn Type= 3
Dn Slope=0.012463
DSS Import GetInterval= 0
DSS Import GetPeak= 0
DSS Import FillOption= 0

--- INDIANDRFT.g01 (geometry) ---

Geom Title=Geometry
Program Version=6.10

River Reach=INDIANDRFT      ,Main
Reach XY= 30
     2233294.728      468165.579     2233942.309      467236.652
     2234132.191      467183.639     2234282.912      466758.374
     2234316.314      466033.3382234546.23396145465547.574355327
      2234079.54      465016.421     2234014.675      464822.333
     2233236.081      464074.276     2232810.459      464043.389
2232716.06873718463704.617223953     2232278.762      463258.717
2231744.41944571 462948.09810704     2231379.177      462860.705
 2231005.4546078461883.455350364     2231044.949      461674.949
2230641.32429241460761.706168096     2230630.215      460531.039
2230297.18533358 460094.53190093     2229995.619      460133.603
     2229807.354       459910.032229784.78958324459074.913096949
2229598.17764954458431.0530744062229634.97363008457493.449004971
2230847.56170482456400.4121342882231142.06134207455338.684616953
     2231778.227      454429.035     2231435.119      453704.784
     2231348.689      453258.998      2230842.67      452836.031

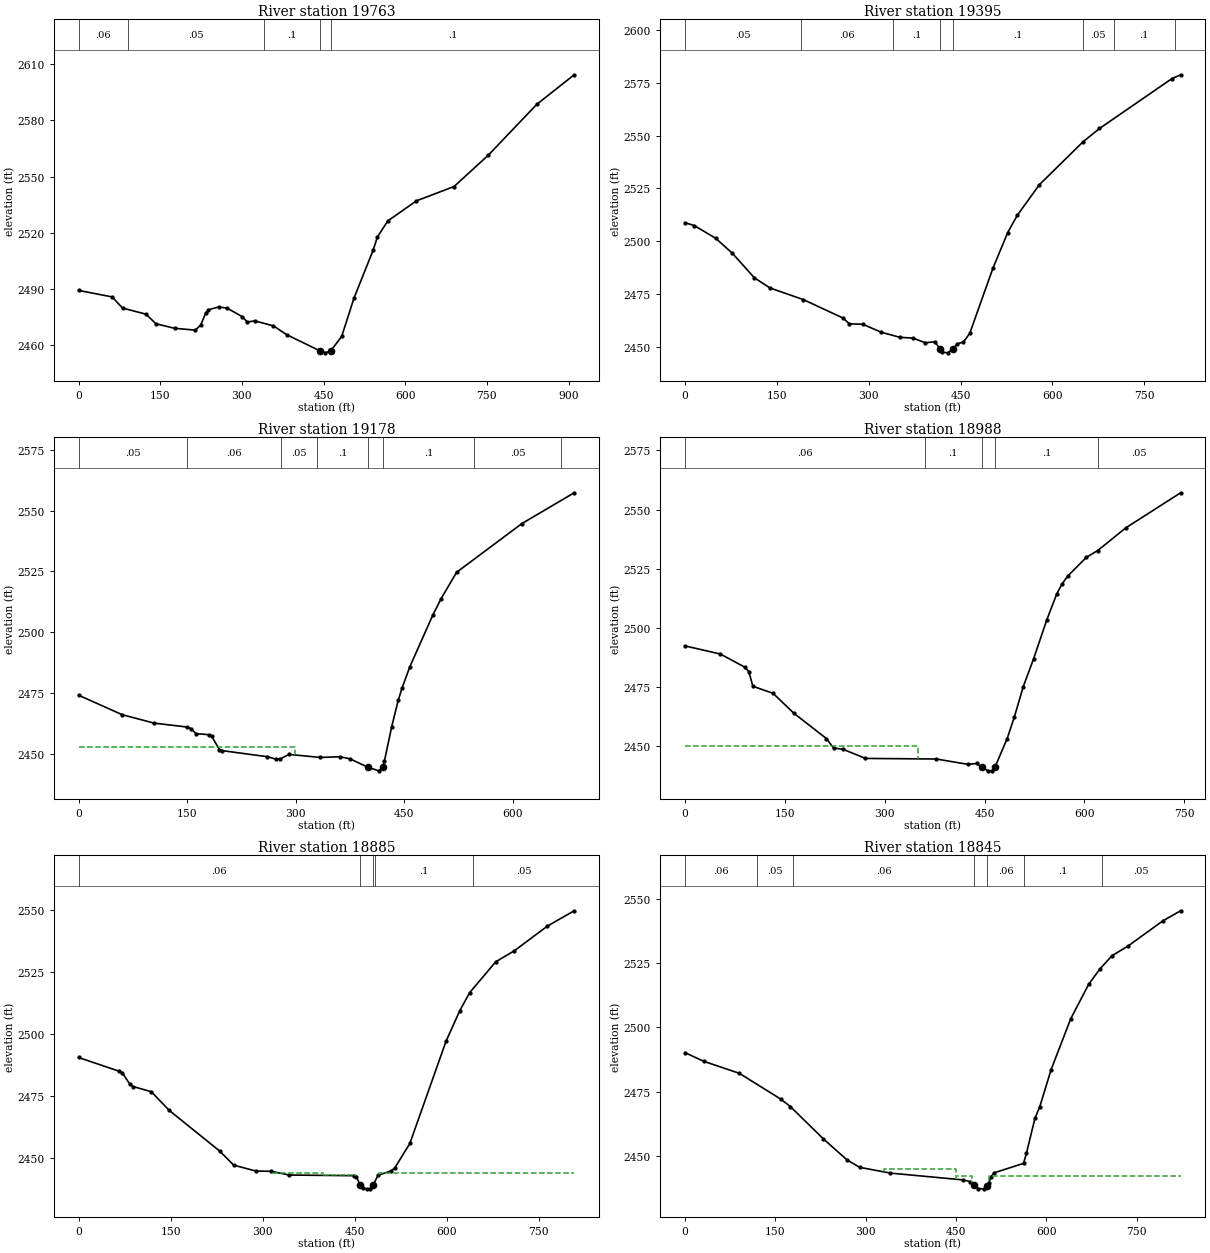
Type RM Length L Ch R = 1 ,19763   ,367.5,367.5,367.5
XS GIS Cut Line= 2
2233679.86705524468406.3618895192232917.80005524467908.548889519
#Sta/Elev= 30
       0 2489.11    61.7  2485.6    80.9 2479.65   123.9 2476.37   142.2 2471.24
   176.4 2468.82   214.5 2467.83   224.2 2470.47   233.7 2476.98   238.5 2478.72
   257.6 2480.25   272.8  2479.6   300.6 2475.07   309.9 2472.21     324 2472.77
     358 2470.12   382.1 2465.43   442.8 2456.84   453.5 2455.69   463.3 2456.79
   483.3 2464.45   506.1 2485.11   541.1 2510.61   549.1 2517.78   568.2 2526.29
   620.7    2537   689.7 2544.65   752.7 2561.45   841.6  2588.6   910.3 2604.43
#Mann= 5 ,-1,0
       0     .06       0      90     .05       0     340      .1       0
   442.8    .045       0   463.3      .1       0
Bank Sta=442.8,463.3
XS Rating Curve= 0 ,0
Exp/Cntr=0.3,0.1

Type RM Length L Ch R = 1 ,19395   ,216.3,217.2,217.6
XS GIS Cut Line= 2
2233851.91037909468136.9027673652233225.68649199467624.065237226
#Sta/Elev= 30
       0 2508.84    15.2 2507.47    50.1 2501.47    77.2 2494.43   113.3 2482.79
   138.9 2477.96   192.9 2472.52   258.3 2463.74   268.5 2460.99     290 2460.85
   320.8 2457.03   351.2 2454.62     372 2454.31   392.6 2452.05   408.1 2452.57
   416.2 2449.24   420.3 2447.69   428.8 2447.31  438.412449.231   444.3 2451.56
   454.6 2452.39     465 2456.49   502.7 2487.18     527 2504.14   542.5 2512.25
   578.7 2526.78   649.8 2546.99   676.9 2553.35     795 2576.89   809.4 2578.74
#Mann= 8 ,-1,0
       0     .05       0     190     .06       0     340      .1       0
   416.2    .045       0  438.41      .1       0     650     .05       0
     700      .1       0     800     .05       0
Bank Sta=416.2,438.41
XS Rating Curve= 0 ,0
Exp/Cntr=0.3,0.1

Type RM Length L Ch R = 1 ,19178   ,190.7,190.5,190.2
XS GIS Cut Line= 3
2233917.03661771467943.4295424792233524.86239135467591.602458743
2233390.90987781467507.680402072
#Sta/Elev= 30
       0    2474    60.3 2465.99   104.2 2462.52   149.5 2460.92   155.2 2460.28
   162.4 2458.17   180.7 2457.73   183.9 2457.12   194.8 2451.62   197.7 2451.22
   260.9 2448.69   272.9 2447.67   278.9 2447.79   290.9 2449.63   334.3 2448.38
   361.2 2448.67   374.8 2447.85   399.7 2444.38   414.9 2442.87   420.3 2444.29
   422.7 2446.88   432.8 2461.09   441.8  2471.9   446.9 2476.78   457.9 2485.77
   489.4 2506.85   500.7 2513.56   522.4 2524.57   612.6 2544.62   684.9 2557.31
#Mann= 8 ,-1,0
       0     .05       0     150     .06       0     280     .05       0
     330      .1       0   399.7    .045       0   420.3      .1       0
  546.86     .05       0  666.86      .1       0
#XS Ineff= 2 , 0
          299.83 2452.71
Permanent Ineff=
       F       F
Bank Sta=399.7,420.3
XS Rating Curve= 0 ,0
Exp/Cntr(USF)=0,0
Exp/Cntr=0.3,0.1

Type RM Length L Ch R = 1 ,18988   ,95.4,102.6,109.6
BEGIN DESCRIPTION:
structure xs 4
END DESCRIPTION:
XS GIS Cut Line= 2
2234075.77362732467824.4527318272233516.40544125467333.218114286
#Sta/Elev= 30
       0  2492.4    53.1 2488.95    89.8 2483.42    95.9  2481.5     102 2475.32
   132.3 2472.35   163.6 2463.91   212.4 2453.24   223.1 2449.23   237.3 2448.72
     271 2444.84   377.4 2444.59   425.3 2442.32   438.5 2442.71  445.352441.167
   455.5 2439.59   461.2  2439.7   465.7 2441.23   483.9 2453.25   494.6 2462.28
   508.1 2475.23   523.6 2486.94   543.4 2503.41   558.4  2514.4   566.1 2518.49
   574.8 2521.89   602.9 2529.82   619.9  2532.7   662.4 2542.34   744.4  2557.1
#Mann= 5 ,-1,0
       0     .06       0     360      .1       0  445.35    .045       0
   465.7      .1       0     620     .05       0
#XS Ineff= 2 , 0
             350    2450
Permanent Ineff=
       F       F
Bank Sta=445.35,465.7
XS Rating Curve= 0 ,0
Exp/Cntr(USF)=0,0
Exp/Cntr=0.5,0.3

Type RM Length L Ch R = 1 ,18885   ,39.3,40.5,39.8
BEGIN DESCRIPTION:
structure xs 3; 9 ft between structure and xs
END DESCRIPTION:
XS GIS Cut Line= 4
2234097.24424855467817.9057919132233875.88423131467611.920812607
2233783.57639405467390.3820031862233583.91987799467215.923152215
#Sta/Elev= 30
       0 2490.56    65.7 2485.06    71.5  2484.3    83.3 2479.87    89.1 2478.82
   118.5 2476.75   147.9 2469.17   230.1 2452.76   252.8  2447.1   288.8 2444.73
     314  2444.6   343.2  2443.1   448.3 2442.84   452.7 2442.33  458.962439.056
   463.3  2437.8   469.4 2437.53   475.5 2437.65  479.952438.923   487.8 2443.02
   509.2 2444.72   515.3    2446   539.8 2455.84   598.9 2497.22   621.3 2509.51
   637.2 2516.72   679.7 2529.18   710.1 2533.64   763.9 2543.59   807.5 2549.78
#Mann= 5 ,-1,0
       0     .06       0  458.96    .045       0  479.95     .06       0
  482.37      .1       0  642.37     .05       0
#XS Ineff= 3 ,-1
  314.56  398.94 2443.74  398.94  449.96    2443   488.9   807.5 2443.75
Permanent Ineff=
       F       F       F
Bank Sta=458.96,479.95
XS Rating Curve= 0 ,0
Exp/Cntr=0.5,0.3

Type RM Length L Ch R = 1 ,18845   ,92.7,84.2,76.9
BEGIN DESCRIPTION:
structure xs 2; 9.9 ft between structure and xs
END DESCRIPTION:
XS GIS Cut Line= 4
2234132.35342309467808.6630866972233910.99340586467602.678107391
 2233818.6855686 467381.139297972233611.27660125467192.474532274
#Sta/Elev= 30
       0 2490.21    30.9 2486.85    90.3 2482.15   158.7 2472.17   175.1  2469.2
   229.7 2456.66   268.6 2448.55   289.8  2445.6   340.9 2443.34   461.7  2440.7
     473 2440.05     480 2438.58     486 2437.34   496.9 2437.22     5022438.515
   504.5 2439.55   507.7 2441.88   513.7 2443.49     562 2447.12   566.8 2451.02
   580.9 2464.62     589 2469.19   607.7 2483.53   640.4 2503.41   670.1 2516.75
   688.5 2522.66   708.8 2527.88     735 2531.59   793.3 2541.46   822.8 2545.38
#Mann= 7 ,-1,0
       0     .06       0     120     .05       0     180     .06       0
     480    .045       0     502     .06       0  562.37      .1       0
  692.37     .05       0
#XS Ineff= 3 ,-1
  330.38     450    2445     450   476.6  2442.1   505.3   822.8  2442.4
Permanent Ineff=
       F       F       F
Bank Sta=480,502
XS Rating Curve= 0 ,0
Exp/Cntr=0.5,0.3

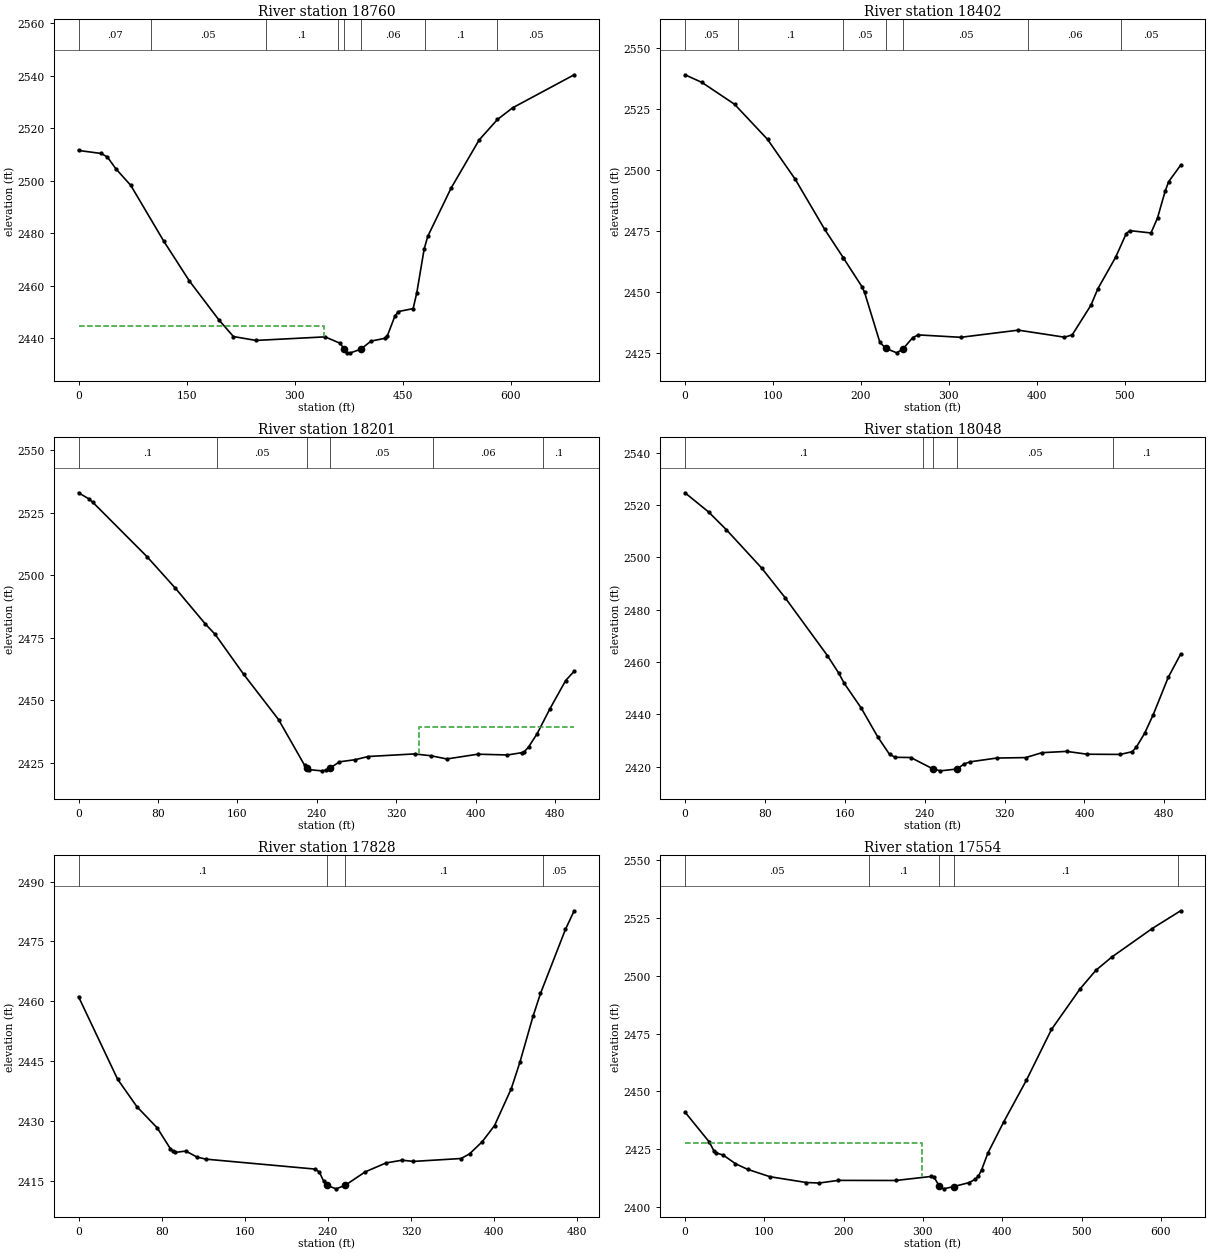
Type RM Length L Ch R = 1 ,18760   ,358.5,358.7,352.6
BEGIN DESCRIPTION:
structure xs 1
END DESCRIPTION:
XS GIS Cut Line= 2
2234185.12379903467593.976216063 2233644.4954795467169.025912333
#Sta/Elev= 30
       0 2511.53    31.7 2510.37    40.1 2509.01    52.1 2504.45    72.5 2498.24
   118.2 2477.04   153.8 2461.87   194.5 2447.14   214.9 2440.72   246.2 2439.24
   342.1  2440.6     363 2438.15   368.7 2435.85   372.6 2434.59   377.3 2434.52
   391.5 2435.89   405.8 2438.99   425.7 2440.08   428.6 2441.11   438.8 2448.42
   443.8 2450.23   464.2 2451.35   469.3 2457.39   479.5 2474.02   484.5 2478.85
   516.8 2497.17   555.8 2515.54   581.2 2523.32   602.3 2527.76   687.6 2540.32
#Mann= 8 ,-1,0
       0     .07       0     100     .05       0     260      .1       0
     360     .06       0   368.7    .045       0   391.5     .06       0
     480      .1       0     580     .05       0
#XS Ineff= 2 , 0
          340.73 2444.76
Permanent Ineff=
       F       F
Bank Sta=368.7,391.5
XS Rating Curve= 0 ,0
Exp/Cntr(USF)=0,0
Exp/Cntr=0.3,0.1

Type RM Length L Ch R = 1 ,18402   ,201.5,200.7,199.5
XS GIS Cut Line= 3
2234358.87544411467259.8952109942233942.03892603467075.934891168
2233834.56608464 467066.16463286
#Sta/Elev= 30
       0 2538.86    19.3 2535.73    56.3 2526.82    93.9 2512.43   125.2 2496.22
   158.8 2475.67     180 2464.06     180 2464.01   201.3 2452.18   204.1 2449.98
   221.6 2429.44   228.6 2426.97   240.7 2425.18   247.8 2426.75   258.9 2431.42
   265.3 2432.51   313.5 2431.53     379 2434.46   431.4 2431.58   440.2 2432.51
   461.5 2444.63   469.5 2451.45   489.6 2464.27   501.7 2473.96   505.7 2475.15
   529.8 2474.18   537.2  2480.3   545.9 2491.29   549.9 2495.17   563.5  2501.9
#Mann= 7 ,-1,0
       0     .05       0      60      .1       0     180     .05       0
   228.6    .045       0   247.8     .05       0     390     .06       0
  495.62     .05       0
Bank Sta=228.6,247.8
XS Rating Curve= 0 ,0
Exp/Cntr=0.3,0.1

Type RM Length L Ch R = 1 ,18201   ,154.1,153.2,149.7
XS GIS Cut Line= 3
2234412.49952921467109.050632884  2234243.210504466988.914594874
 2233968.9630675466889.380776223
#Sta/Elev= 30
       0 2533.08    10.2  2530.7    14.5 2529.24    69.1 2507.48    97.7 2494.85
   127.9 2480.53   137.7 2476.41   166.5 2460.38   201.5 2442.35   227.8 2424.02
   230.3 2422.99   232.1 2422.31   244.9 2421.83   249.1 2422.06   253.7 2422.98
   262.8 2425.43   278.9  2426.3   291.7 2427.56   338.5  2428.6   355.5 2427.84
     371 2426.58   402.3 2428.49   432.1 2428.18   446.9 2429.12   449.1  2429.5
   453.3 2431.33   461.9 2436.62   474.6 2446.45   490.7 2457.94   499.3 2461.68
#Mann= 6 ,-1,0
       0      .1       0     140     .05       0   230.3    .045       0
   253.7     .05       0  357.58     .06       0  467.58      .1       0
#XS Ineff= 2 , 0
                          343.38         2439.52
Permanent Ineff=
       F       F
Bank Sta=230.3,253.7
XS Rating Curve= 0 ,0
Exp/Cntr(USF)=0,0
Exp/Cntr=0.3,0.1

Type RM Length L Ch R = 1 ,18048   ,222.7,219.6,215.9
XS GIS Cut Line= 3
2234452.42694532467006.4184628142234303.64545179466846.557496367
2234032.98975613466783.246222527
#Sta/Elev= 30
       0 2524.68    23.6 2517.36    41.5 2510.55    76.7 2495.96   100.2 2484.63
   142.6 2462.48   153.9 2455.81   159.5 2451.86   176.5 2442.42   192.9 2431.49
   204.8 2424.75   210.5 2423.62   226.1 2423.54   248.12419.224   255.7 2418.45
   272.4 2419.14   279.5 2421.08   285.5 2421.89   312.2 2423.34   341.1 2423.51
   357.5 2425.39   382.2 2425.88   402.7  2424.8   435.7 2424.72   447.9 2425.76
     452 2427.54   460.2 2432.75   468.8 2439.85   483.9 2454.18   496.3 2463.03
#Mann= 5 ,-1,0
       0      .1       0  238.38     .05       0   248.1    .045       0
   272.4     .05       0  428.38      .1       0
Bank Sta=248.1,272.4
XS Rating Curve= 0 ,0
Exp/Cntr(USF)=0,0
Exp/Cntr=0.3,0.1

Type RM Length L Ch R = 1 ,17828   ,274.4,274.7,274.7
XS GIS Cut Line= 4
2234531.65967782466693.2903746522234322.73247415466620.482409736
2234246.75894554466620.4824097362234067.90459694466637.893010042
#Sta/Elev= 30
       0 2461.14    37.6 2440.45    56.2 2433.54    75.7 2428.24    88.4    2423
    90.8 2422.41    92.6 2422.06   103.3 2422.42   113.8 2420.93   122.5 2420.39
   227.8 2417.89   231.8 2417.12   235.8 2414.88   239.1 2413.81   247.8 2412.94
   256.5 2413.81   275.8 2417.19   295.8 2419.43   311.2 2420.12   322.2 2419.82
   368.1 2420.55   376.2  2421.7   388.4 2424.75   400.3 2428.82   416.4 2438.07
   424.7  2444.7   437.3 2456.21   444.5 2461.95   468.5 2478.02   476.9 2482.69
#Mann= 4 ,-1,0
       0      .1       0   239.1    .045       0   256.5      .1       0
  447.22     .05       0
Bank Sta=239.1,256.5
XS Rating Curve= 0 ,0
Exp/Cntr(USF)=0,0
Exp/Cntr=0.3,0.1

Type RM Length L Ch R = 1 ,17554   ,220.5,223.9,227.3
XS GIS Cut Line= 4
2234594.87246846466446.0396011312234512.76466068466369.764896803
2234324.41799783466346.4920732352234001.24669138466343.868976617
#Sta/Elev= 30
       0 2440.98    30.7 2427.99    36.4 2424.21    39.3 2423.29    48.3 2422.33
    63.7  2418.6    78.9 2416.18   107.2 2412.97     153 2410.46   169.1 2410.24
   193.3 2411.38   265.8 2411.34   310.1 2413.07   314.1 2412.73320.88852408.786
   326.1 2407.72339.08852408.719   358.1 2410.41   366.1 2411.84   370.1 2413.29
   374.1    2416   382.1 2423.32   402.1 2436.83   430.4  2454.7   462.1 2476.75
   498.1 2494.31   518.1 2502.38   538.1 2508.11   589.1 2520.48     625 2528.18
#Mann= 5 ,-1,0
       0     .05       0  232.07      .1       0320.8885    .045       0
339.0885      .1       0  621.85     .05       0
#XS Ineff= 2 , 0
          299.32 2427.66
Permanent Ineff=
       F       F
Bank Sta=320.8885,339.0885
XS Rating Curve= 0 ,0
Exp/Cntr=0.3,0.1

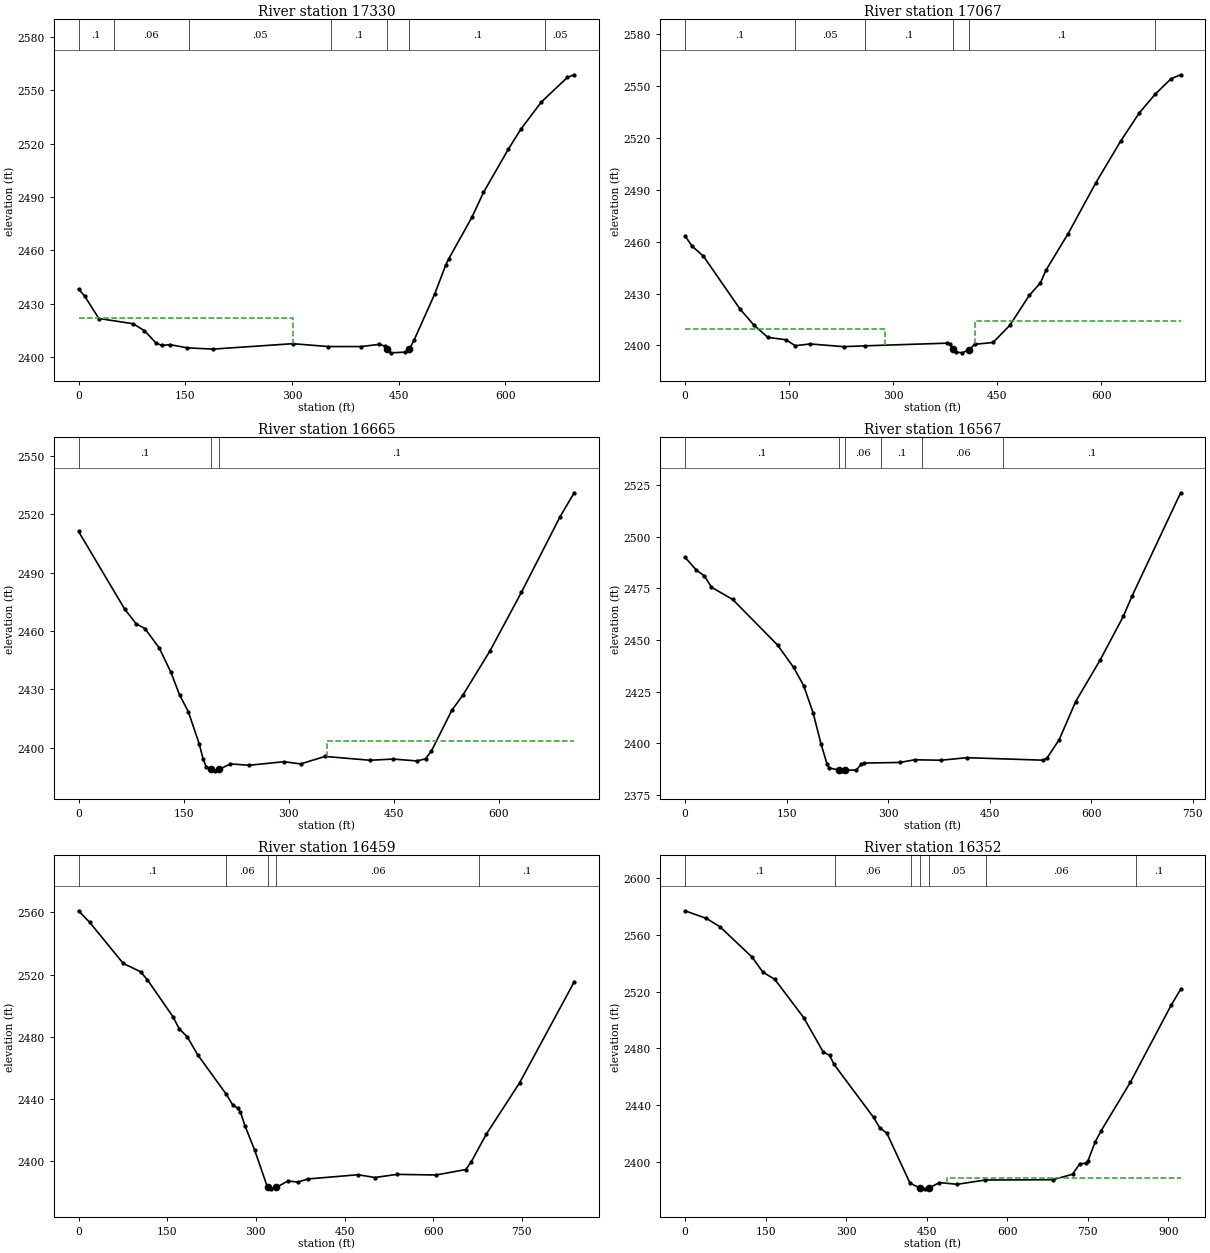
Type RM Length L Ch R = 1 ,17330   ,257.2,262.5,268.2
XS GIS Cut Line= 5
2234740.66660122466160.5849118542234616.34273484466169.061695588
2234446.58058773466170.5508372292234330.42753971466133.322296196
2234054.86142205466081.637460208
#Sta/Elev= 30
       0  2438.3     8.5 2434.41    28.6 2421.73    76.7  2418.8    92.7 2414.89
   108.7 2408.06   116.8 2406.63   128.8 2407.03   152.7 2405.26   188.8 2404.53
   301.1 2407.58   351.3 2405.97   397.7 2405.98   422.7  2407.2   430.9 2406.21
     434 2404.48     439 2402.44   459.1 2402.84     4652404.533   471.6 2409.51
   500.7 2435.54   516.3 2451.88   520.4 2455.24   552.9 2478.56   569.2 2492.54
   604.3 2516.96   622.1 2528.31   650.6 2543.38   687.2 2557.22   696.7 2558.67
#Mann= 7 ,-1,0
       0      .1       0      50     .06       0  154.61     .05       0
  354.38      .1       0     434    .045       0     465      .1       0
  656.35     .05       0
#XS Ineff= 2 , 0
           301.3 2422.01
Permanent Ineff=
       F       F
Bank Sta=434,465
XS Rating Curve= 0 ,0
Exp/Cntr=0.3,0.1

Type RM Length L Ch R = 1 ,17067   ,409.5,402.2,386.7
XS GIS Cut Line= 5
2234742.54422416465973.5928357442234625.04380674465988.484252157
2234389.16590445465885.7938633712234335.10470667465856.672462816
2234058.31426566465869.981097383
#Sta/Elev= 30
       0 2463.44    10.5 2457.35    26.6 2451.65      79 2421.22    99.2 2411.83
   119.4 2404.67   145.6 2403.28   158.7 2399.87   180.5 2400.86   228.5  2399.3
     259 2399.77   376.9 2401.31   381.4 2400.99   386.5 2397.76   390.5 2396.23
   399.5 2395.72   409.4 2397.59   417.7 2400.68   443.9 2401.71   468.1 2411.66
   496.1 2428.97   512.1 2436.17   520.1  2443.5   552.2 2464.78   592.2 2494.24
   627.6 2518.13   654.2 2534.33   677.3 2545.29   700.3 2554.32   714.2 2556.63
#Mann= 6 ,-1,0
       0      .1       0   158.7     .05       0     259      .1       0
   386.5    .045       0   409.4      .1       0   677.3     .05       0
#XS Ineff= 2 , 0
       0     288 2409.48     418       0 2414.14
Permanent Ineff=
       F       F
Bank Sta=386.5,409.4
XS Rating Curve= 0 ,0
Exp/Cntr(USF)=0,0
Exp/Cntr=0.3,0.1

Type RM Length L Ch R = 1 ,16665   ,101,98.4,93.9
XS GIS Cut Line= 5
 2234720.1874421 465479.227060752234581.61957544465513.436101415
2234489.77914734465542.7468763412234374.49009929465617.000839487
2234056.61241643465710.419219684
#Sta/Elev= 30
       0 2511.18    65.9 2471.26    82.4 2463.64    94.8 2461.27   115.4 2451.18
   131.9  2438.8   144.2 2427.23   156.8 2418.51   172.3 2402.03   177.8 2394.41
     182 2390.38  189.08 2389.02   194.6 2388.16     201 2388.97   216.9 2391.71
   243.6 2391.03   293.4 2392.85   317.2 2391.72     352 2395.56   416.2 2393.59
   449.2 2394.21   482.9 2393.25   495.4 2394.32   503.8 2398.34   532.9 2419.22
   549.1 2427.28   587.1 2449.57   632.3 2479.88   687.6  2518.8   707.6 2531.01
#Mann= 3 ,-1,0
       0      .1       0  189.08    .045       0     201      .1       0
#XS Ineff= 2 , 0
                          355.15         2403.41
Permanent Ineff=
       F       F
Bank Sta=189.08,201
XS Rating Curve= 0 ,0
Exp/Cntr=0.3,0.1

Type RM Length L Ch R = 1 ,16567   ,111,107.8,104
XS GIS Cut Line= 3
2234688.57479266465316.3385284372234234.43703853465602.233539458
2234054.42906863465678.707513599
#Sta/Elev= 30
       0 2490.09    16.6 2483.91    28.8 2481.04    39.1 2475.58    70.5 2469.64
   136.7 2447.63   160.4 2436.81   175.4 2427.95   189.3  2414.8     201 2399.72
   209.7 2390.23   213.2 2388.18   228.2 2387.07   232.1 2386.77   236.8 2387.03
   253.3 2387.24   260.4 2389.99   264.9 2390.53   317.2 2390.82   339.4 2392.12
     378  2391.9   416.4 2393.13   528.8 2391.93   534.7 2392.89   552.8 2401.86
   577.2  2420.3     613 2440.19   647.4 2461.42   660.8 2471.56   732.2 2521.25
#Mann= 6 ,-1,0
       0      .1       0   228.2    .045       0   236.8     .06       0
     290      .1       0     350     .06       0     470      .1       0
Bank Sta=228.2,236.8
XS Rating Curve= 0 ,0
Exp/Cntr(USF)=0,0
Exp/Cntr=0.3,0.1

Type RM Length L Ch R = 1 ,16459   ,106.2,106.7,106.4
XS GIS Cut Line= 5
 2234682.4672144465126.9112179652234464.14572909465321.398479988
2234394.54979709465390.0410430552234377.38915633465445.336441081
2234045.61676817465651.264130282
#Sta/Elev= 30
       0 2561.05    19.1 2553.53    75.6 2527.24   104.9 2521.87   116.6 2516.65
   159.8 2492.93   170.4 2485.12   183.8 2480.13   201.5  2468.5     250 2443.08
     261 2436.12   269.5 2434.07     274 2431.55   281.6 2422.77     298  2407.2
  319.78 2383.21   326.1 2382.28   334.6 2383.17   354.1 2387.33   371.4 2386.63
   387.9 2388.63     473 2391.35   501.3 2389.56   538.9 2391.59   604.8 2391.18
     655 2394.68   663.8 2399.24   689.9 2417.44   746.1 2450.39   838.5 2515.29
#Mann= 5 ,-1,0
       0      .1       0     250     .06       0  319.78    .045       0
   334.6     .06       0  678.03      .1       0
Bank Sta=319.78,334.6
XS Rating Curve= 0 ,0
Exp/Cntr(USF)=0,0
Exp/Cntr=0.3,0.1

Type RM Length L Ch R = 1 ,16352   ,303,305.3,307.1
XS GIS Cut Line= 2
2234667.05583753464975.5715286082234011.87950913465625.345613504
#Sta/Elev= 30
       0 2577.12    39.9 2571.72    65.4 2565.76   124.8 2544.46   144.9 2533.87
   167.4 2528.62     221 2501.69   257.7 2477.24   269.3 2475.04   277.5 2468.66
   351.1 2431.22   362.4 2424.09   375.9    2420     419 2384.78   437.8 2381.38
   447.2 2380.82   454.7 2381.48   473.8 2385.24   506.6 2384.03     559 2387.05
   684.8 2387.25   721.6 2391.12   735.1  2398.6   746.4 2398.76   749.9 2400.34
     764 2414.23   774.8 2421.85   829.1 2456.05   905.4 2510.72   922.7 2521.66
#Mann= 7 ,-1,0
       0      .1       0     280     .06       0     420     .05       0
   437.8    .045       0   454.7     .05       0     560     .06       0
     840      .1       0
#XS Ineff= 2 , 0
                          488.23         2388.73
Permanent Ineff=
       F       F
Bank Sta=437.8,454.7
XS Rating Curve= 0 ,0
Exp/Cntr=0.3,0.1

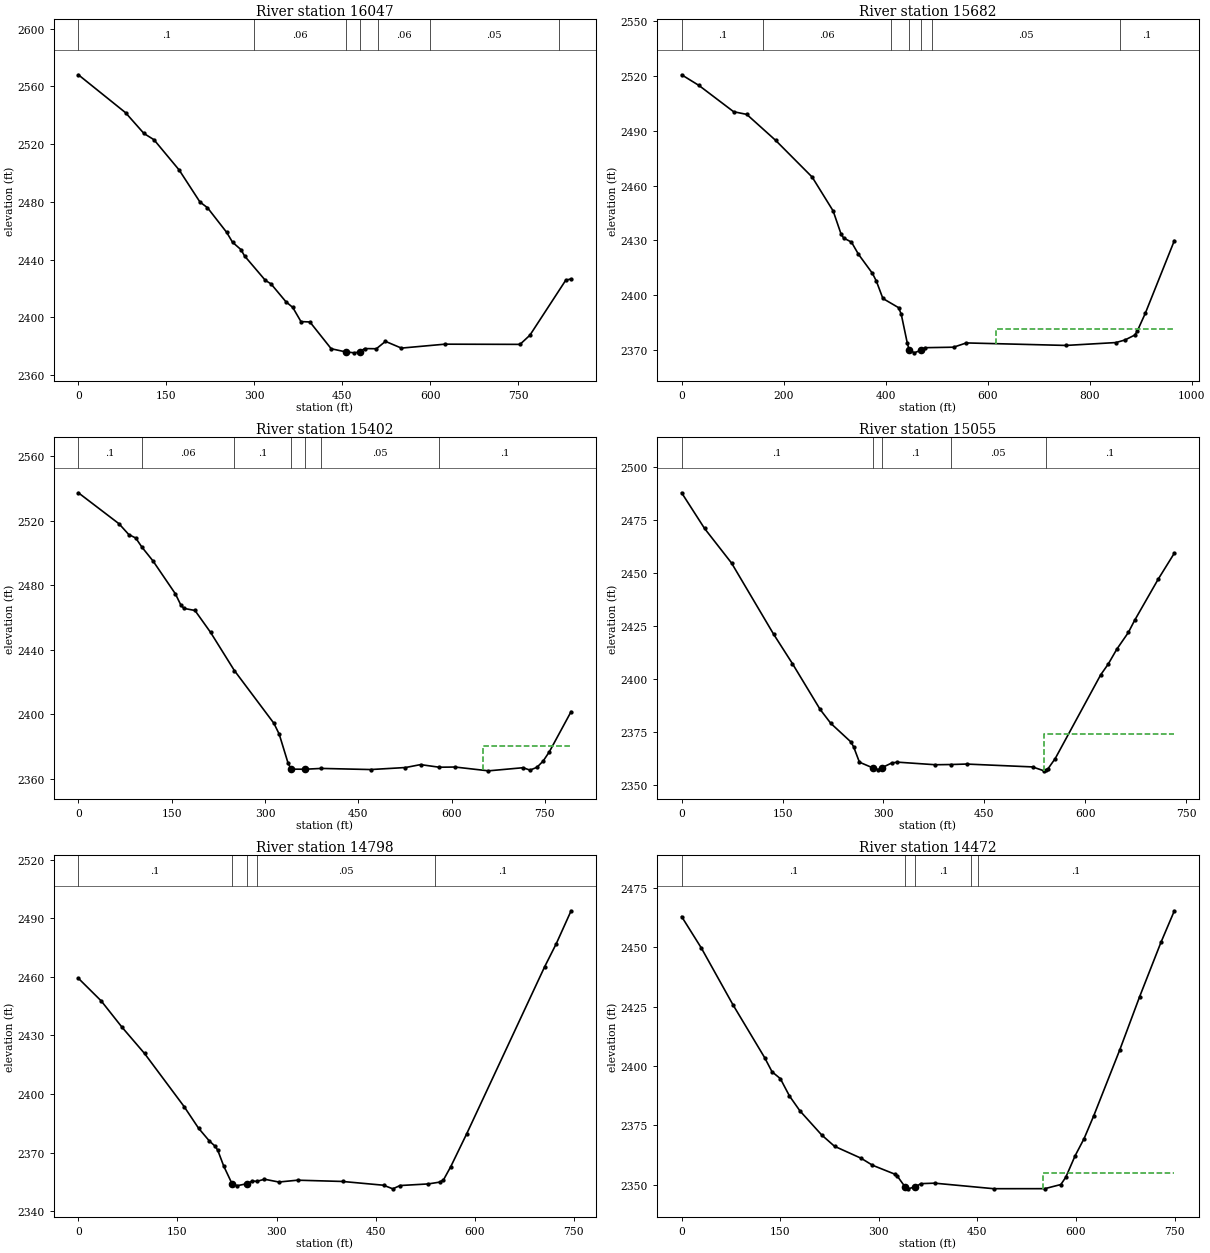
Type RM Length L Ch R = 1 ,16047   ,365.4,364.5,365
XS GIS Cut Line= 3
 2234499.9104007464792.1066602552234082.05599335465116.576938686
2233888.95660814 465360.32534297
#Sta/Elev= 30
       0    2568    80.4 2541.77   111.8 2527.36   128.9 2523.03   171.9 2502.03
   207.3 2479.89   220.1 2475.96   252.9 2458.85   262.8 2452.06   277.1 2446.97
   283.3 2442.58   318.7 2425.68   328.4 2423.22   353.9 2410.82   365.5 2406.91
   379.5 2397.09   394.7 2396.86     431 2378.31   455.5 2376.14   470.6 2375.47
   479.5 2376.15     488 2378.43     508  2378.3   523.5 2383.41   550.7 2378.75
   624.8 2381.47   752.9 2381.33   769.7 2387.65   830.9 2425.78     840 2426.66
#Mann= 7 ,-1,0
       0      .1       0     300     .06       0   455.5    .045       0
   479.5     .05       0     510     .06       0  599.04     .05       0
  819.04      .1       0
Bank Sta=455.5,479.5
XS Rating Curve= 0 ,0
Exp/Cntr(USF)=0,0
Exp/Cntr=0.3,0.1

Type RM Length L Ch R = 1 ,15682   ,282.4,280.4,279.3
XS GIS Cut Line= 3
2234323.64408882464475.8900705842233848.98850942464857.740848664
 2233649.2480003 465153.50484189
#Sta/Elev= 30
       0 2520.76      34 2514.91     102 2500.51   127.7 2499.05   184.1 2484.88
     256 2464.68   297.1 2446.13   312.5 2433.56   317.6 2431.33     333 2429.05
   346.7 2422.41   374.1 2411.94   381.8  2407.7   394.6 2398.17   425.4 2393.13
   430.6 2389.54   442.4 2373.79     446 2370.19   456.2 2368.38     470 2369.94
   476.8  2371.2   533.2 2371.47   558.2 2373.81   753.6 2372.44   851.4 2374.01
   869.2 2375.42   888.5 2378.13   893.3 2380.25     909 2389.97   966.1 2429.89
#Mann= 7 ,-1,0
       0      .1       0     160     .06       0     410      .1       0
     446    .045       0     470      .1       0     490     .05       0
  859.19      .1       0
#XS Ineff= 2 , 0
                          616.78         2381.25
Permanent Ineff=
       F       F
Bank Sta=446,470
XS Rating Curve= 0 ,0
Exp/Cntr=0.3,0.1

Type RM Length L Ch R = 1 ,15402   ,348.1,346.9,346.5
XS GIS Cut Line= 2
2234026.45328174464314.9299483362233456.65181717464865.386301447
#Sta/Elev= 30
       0 2537.25    65.4 2518.03      81 2511.38    92.2 2509.22   102.2 2503.55
     120 2494.99     156  2474.6     165 2467.49     170 2465.57   187.5 2464.28
   212.5 2450.75   250.8 2427.07   314.4 2394.35   322.9 2387.65   337.1 2369.76
  342.062365.918   364.7 2365.87   390.8 2366.37     470 2365.67     526 2366.92
   550.2 2368.73   580.3 2367.11   605.7 2367.23   659.4 2364.87   715.1 2366.81
   726.2 2365.32   737.3 2367.05   747.2 2370.85   757.4 2376.74   792.3 2401.59
#Mann= 7 ,-1,0
       0      .1       0   102.2     .06       0   250.8      .1       0
  342.06    .045       0   364.7      .1       0   390.8     .05       0
   580.3      .1       0
#XS Ineff= 2 , 0
                             650            2380
Permanent Ineff=
       F       F
Bank Sta=342.06,364.7
XS Rating Curve= 0 ,0
Exp/Cntr(USF)=0,0
Exp/Cntr=0.3,0.1

Type RM Length L Ch R = 1 ,15055   ,255.3,256.8,255.9
XS GIS Cut Line= 2
2233691.95826555464159.2431697932233180.42042053 464683.55212537
#Sta/Elev= 30
       0 2487.71    34.1 2470.86    74.2 2454.55   136.8 2420.94   164.8 2407.03
   205.9 2385.46   221.8 2378.87   251.7 2370.09   255.8 2367.72   264.3 2360.56
   284.1 2357.88   292.6 2357.06   297.5 2357.91   312.4 2360.19   320.9 2360.57
   377.1 2359.35   400.1 2359.45   423.6 2359.67   521.7 2358.32   538.7 2356.47
   541.5 2356.82   544.8 2357.53   555.3 2362.23     623  2401.8   634.2 2406.87
   646.9 2413.87   664.1 2421.78   673.3 2427.43   708.4  2446.9   732.5 2459.23
#Mann= 5 ,-1,0
       0      .1       0   284.1    .045       0   297.5      .1       0
   400.1     .05       0   541.5      .1       0
#XS Ineff= 2 , 0
                          538.21         2373.98
Permanent Ineff=
       F       F
Bank Sta=284.1,297.5
XS Rating Curve= 0 ,0
Exp/Cntr=0.3,0.1

Type RM Length L Ch R = 1 ,14798   ,335.4,326.6,311.2
XS GIS Cut Line= 2
2233513.69556792464005.8133243212232966.07862074464512.419310699
#Sta/Elev= 30
       0 2459.28    34.6 2447.68    65.7 2434.37   100.2 2420.76   160.1 2393.57
   181.9 2382.52   198.2 2375.99   207.3 2373.19   211.1 2371.16     220 2363.15
   232.7 2354.02   240.6 2353.05   255.4 2354.08   263.6 2355.49     270 2355.25
   281.8 2356.36   303.5 2354.93   331.8 2355.87   399.9 2355.22     462 2353.29
   476.1 2351.44     487 2353.13   529.9 2353.96   546.9 2354.88   552.8 2356.04
   563.9 2362.88   588.1 2379.76   705.9 2465.15   723.6 2477.04     746 2493.85
#Mann= 5 ,-1,0
       0      .1       0   232.7    .045       0   255.4      .1       0
     270     .05       0     540      .1       0
Bank Sta=232.7,255.4
XS Rating Curve= 0 ,0
Exp/Cntr(USF)=0,0
Exp/Cntr=0.3,0.1

Type RM Length L Ch R = 1 ,14472   ,259.3,271.4,284.6
XS GIS Cut Line= 4
 2233296.5891406463767.1753980122233063.18852545463983.206665062
2233064.27410971 464046.170551942232823.27440476464325.165705868
#Sta/Elev= 30
       0 2463.03      30 2449.77    78.1 2425.85   126.3 2403.56   137.6 2397.58
   150.2 2394.71   164.1 2387.39     180 2381.12   213.1 2370.96   232.6  2366.2
   273.1 2361.14   290.4  2358.2     324 2354.48     328 2353.67     340 2349.07
     344 2348.25   355.7 2349.09     364 2350.44     385 2350.64   474.8 2348.31
   552.5 2348.32     577 2350.07   584.6  2353.2   598.7  2362.2   612.3 2369.41
   627.1 2379.09   666.8 2406.95   696.8 2429.22   729.2  2452.1   749.7 2465.47
#Mann= 5 ,-1,0
       0      .1       0     340    .045       0   355.7      .1       0
  441.01     .05       0  451.01      .1       0
#XS Ineff= 2 , 0
                             550            2355
Permanent Ineff=
       F       F
Bank Sta=340,355.7
XS Rating Curve= 0 ,0
Exp/Cntr(USF)=0,0
Exp/Cntr=0.3,0.1