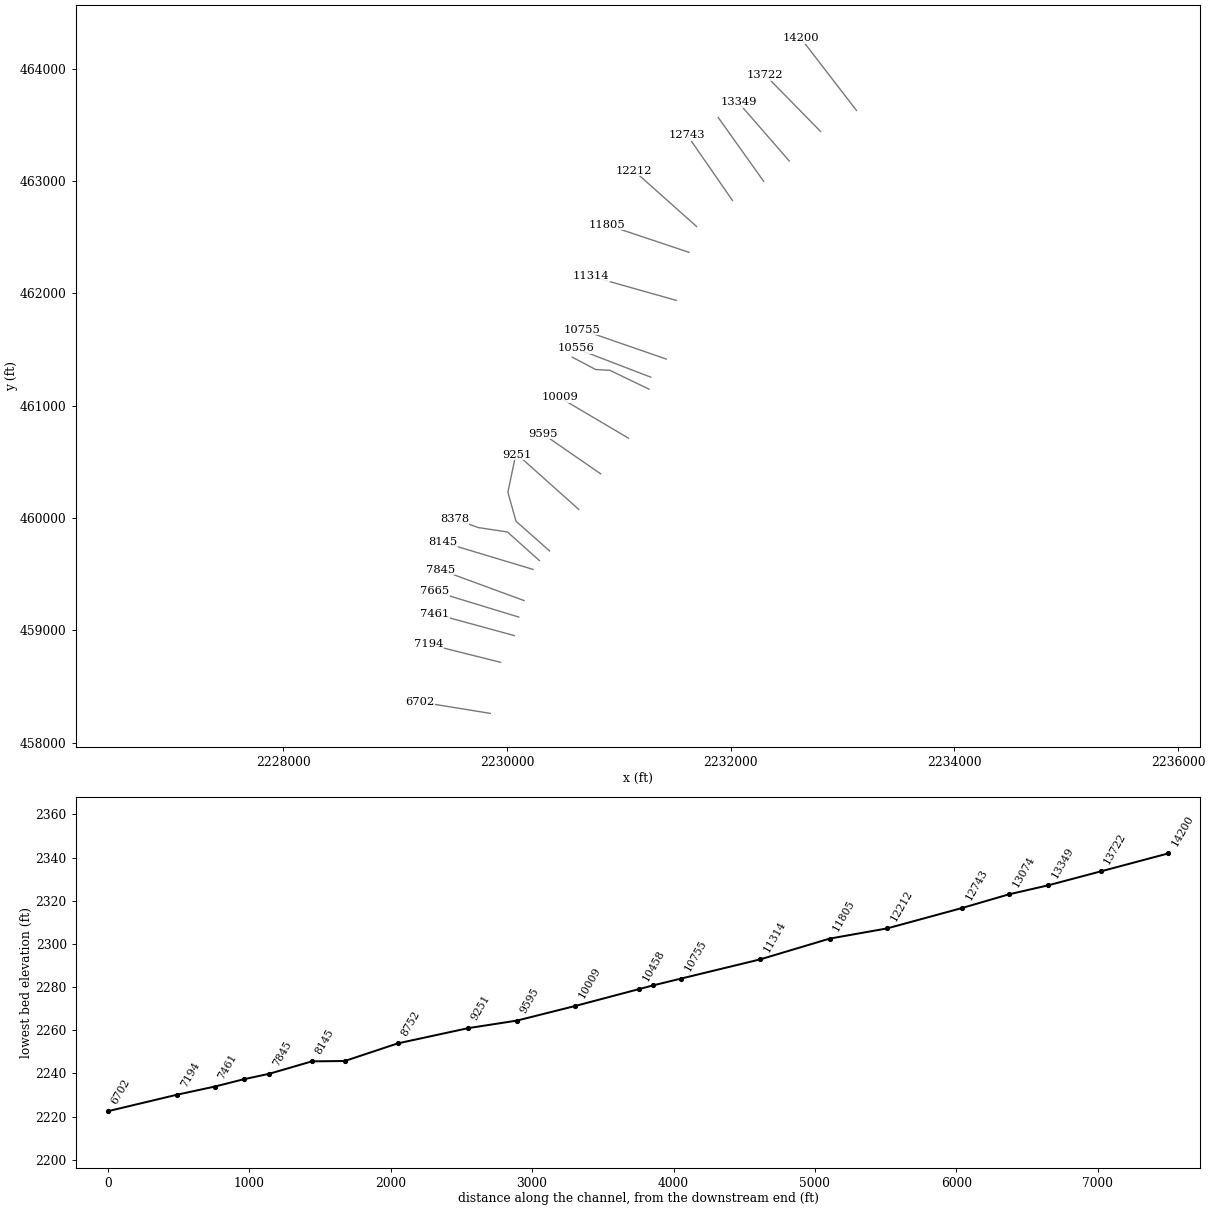
HEC-RAS study INDIANDRFT.prj: INDIANDRFT

--- INDIANDRFT.g01 (geometry) --- (continued)

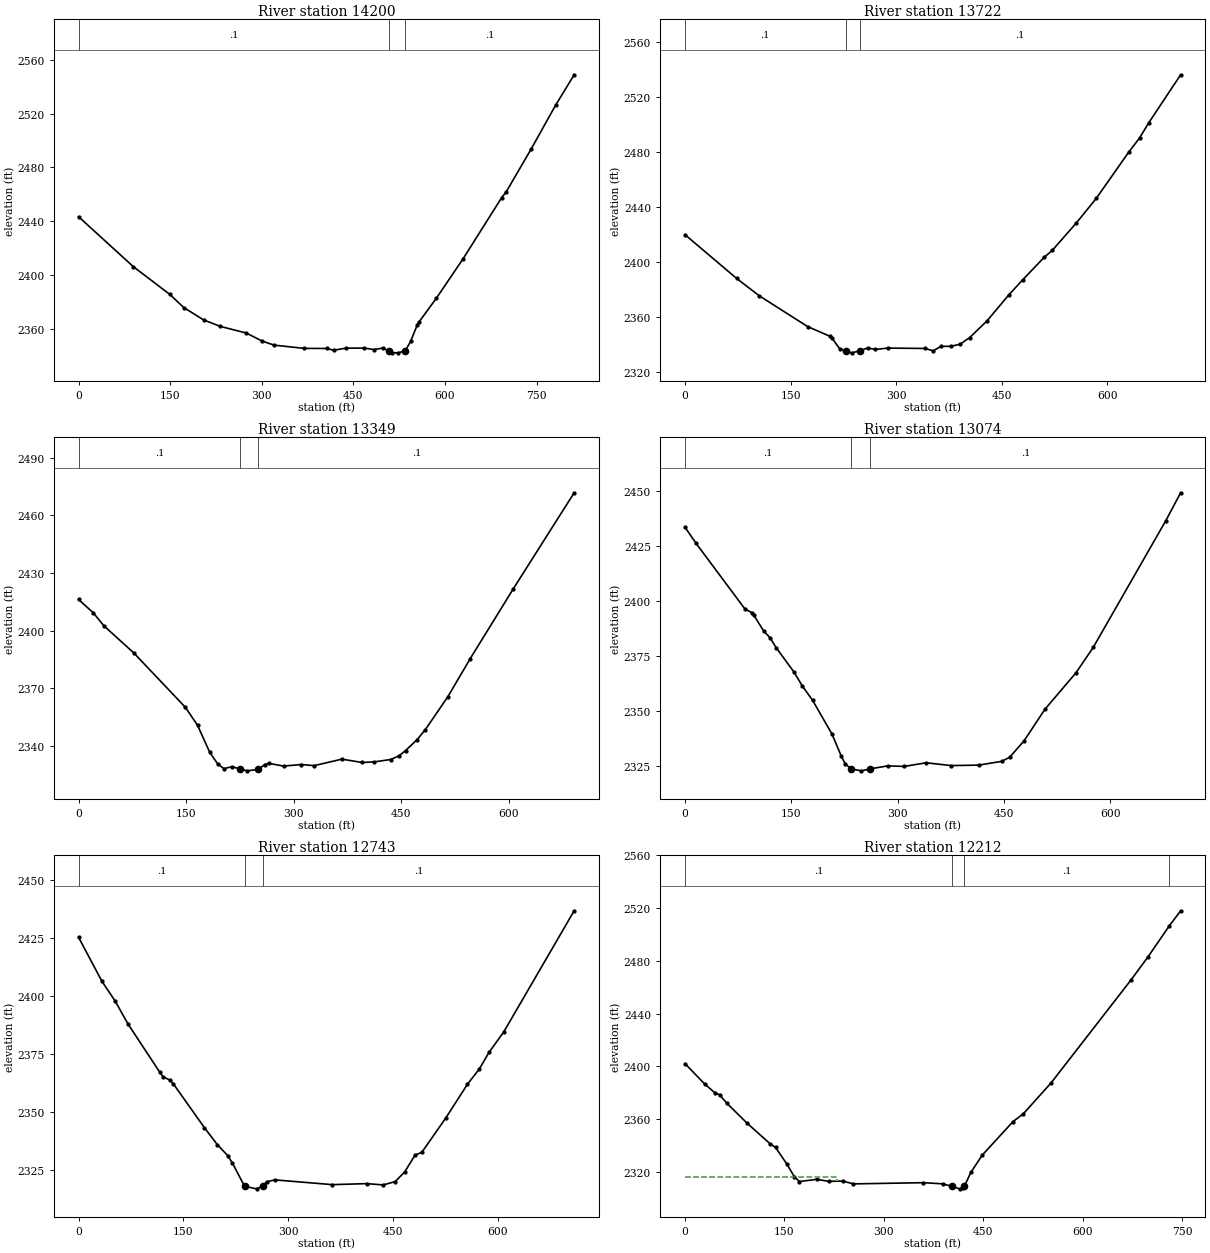
Type RM Length L Ch R = 1 ,14200   ,475,478.1,481.5
XS GIS Cut Line= 2
2233123.92596677 463627.043498192232627.65723231 464268.97931721
#Sta/Elev= 30
       0 2443.38    89.7 2406.17   149.6 2385.43   172.4 2375.69   204.9 2366.46
   232.3 2361.64   274.3 2356.77     301 2350.66   320.1 2347.71   369.2  2345.3
   406.3 2345.21   417.7 2343.93   437.5 2345.43   467.8 2345.52   483.6  2344.4
   498.2 2345.53   508.9 2343.23   513.3 2342.07   522.8 2341.97   534.6 2343.29
   543.7 2350.51   554.5 2362.72   557.4 2364.96   585.9 2382.69   629.6 2412.06
   692.8 2457.62     700 2461.75   740.9 2493.68   781.3 2526.64   811.4 2549.05
#Mann= 3 ,-1,0
       0      .1       0   508.9    .045       0   534.6      .1       0
Bank Sta=508.9,534.6
XS Rating Curve= 0 ,0
Exp/Cntr=0.3,0.1

Type RM Length L Ch R = 1 ,13722   ,373.5,373.1,371.3
XS GIS Cut Line= 2
 2232802.4013898463440.8586496762232308.27621277463942.756620061
#Sta/Elev= 30
       0 2419.79    73.4 2387.87   105.8 2375.14   174.3 2352.78   205.5 2345.83
   208.4 2344.76   219.6 2336.69   228.1 2334.99   236.9 2333.63   248.3 2335.05
   259.7  2337.2   270.5 2336.11   288.2 2337.09   341.2 2336.82   352.5 2335.11
   363.9 2338.34     378  2338.4   390.9 2339.92   404.6 2344.79   428.9 2356.78
     460 2375.78   479.8 2386.83   510.6 2403.36     522 2408.36   556.2 2428.39
   584.5 2446.31   630.3 2479.79     646 2490.34   658.8  2501.2   704.3 2536.36
#Mann= 3 ,-1,0
       0      .1       0   228.1    .045       0   248.3      .1       0
Bank Sta=228.1,248.3
XS Rating Curve= 0 ,0
Exp/Cntr=0.3,0.1

Type RM Length L Ch R = 1 ,13349   ,275.6,274.8,272.3
XS GIS Cut Line= 2
2232522.83273024463177.7510994432232068.29365653463698.239656534
#Sta/Elev= 30
       0 2416.25    20.5 2409.36    35.5 2402.53      77 2388.48   148.9 2360.22
   165.9 2350.88   182.9  2336.8   194.3 2330.59   202.8 2328.31   214.1 2329.32
   225.4 2328.07   235.1 2327.15   250.9 2327.88   259.4 2330.37   265.5 2331.03
     286 2329.62   310.5 2330.44   328.5 2329.85   367.2 2333.23   395.5 2331.49
   412.5 2331.81   435.2 2333.04   446.6  2334.9     456  2337.7   471.9 2343.33
   483.4 2348.51   514.9 2365.69   546.2 2385.56   606.1 2421.78     691 2471.73
#Mann= 3 ,-1,0
       0      .1       0   225.4    .045       0   250.9      .1       0
Bank Sta=225.4,250.9
XS Rating Curve= 0 ,0
Exp/Cntr=0.3,0.1

Type RM Length L Ch R = 1 ,13074   ,330.4,331.5,330
XS GIS Cut Line= 2
2232294.46630981462996.3866505592231887.91236181 463565.03927879
#Sta/Elev= 30
       0 2433.76    15.7 2426.38    84.6 2396.56    94.4 2394.91    96.8 2393.91
   111.2 2386.46   119.8  2383.6   128.8 2378.89   153.4 2368.07   165.6 2361.54
     180 2355.07   207.5 2339.61   220.1 2329.95   225.9  2326.2   234.5 2323.89
   248.8 2323.02   261.6 2323.96   286.1 2325.28     309 2325.03   340.3 2326.68
   375.3 2325.41     414 2325.62   446.6 2327.33   457.9  2329.2   478.2 2336.66
   507.4 2350.91   551.7  2367.7   575.7  2379.1     678 2436.67     699 2449.39
#Mann= 3 ,-1,0
       0      .1       0   234.5    .045       0   261.6      .1       0
Bank Sta=234.5,261.6
XS Rating Curve= 0 ,0
Exp/Cntr(USF)=0,0
Exp/Cntr=0.3,0.1

Type RM Length L Ch R = 1 ,12743   ,528.4,531,533.3
XS GIS Cut Line= 2
2232015.61200362462826.052391247     2231610.686      463408.098
#Sta/Elev= 30
       0 2425.24    33.5  2406.2    52.5 2397.64    70.8 2387.79   115.9 2367.13
   120.8 2365.05   130.5 2363.61   135.4 2362.08     180  2343.1   198.7 2335.71
   213.3 2331.05   220.2 2327.79   237.5 2317.79   254.7 2316.68   263.3 2317.95
   269.1  2319.7   280.6 2320.55   363.2 2318.49   412.3 2318.93   435.8 2318.37
     453 2319.81   466.7 2324.02   481.3  2331.2   491.1 2332.44   525.2 2347.16
   556.4 2361.82   573.4 2368.41   587.4 2375.64   608.4 2384.43     709 2436.62
#Mann= 3 ,-1,0
       0      .1       0   237.5    .045       0   263.3      .1       0
Bank Sta=237.5,263.3
XS Rating Curve= 0 ,0
Exp/Cntr=0.3,0.1

Type RM Length L Ch R = 1 ,12212   ,399.9,406.1,411.4
XS GIS Cut Line= 2
 2231694.3519211462594.5909722222231134.98711056463090.681800592
#Sta/Elev= 30
       0 2402.08    29.6 2386.72    45.7 2379.69    52.1 2378.53    62.9  2372.2
      94 2356.82     128 2341.53   136.6 2338.59   153.6 2326.06   164.9 2316.44
   172.7 2312.76   198.9 2314.39   216.8 2312.89   238.2 2313.06   254.2 2310.97
   359.6 2311.87   388.7 2311.01   402.9 2309.06   414.2 2307.21   419.9 2307.81
  421.312309.064   431.2 2319.62   448.2 2332.61   494.8 2358.14   510.6 2364.15
   552.5 2387.61   673.1 2465.65     698  2482.6     730 2506.04   747.7 2517.88
#Mann= 4 ,-1,0
       0      .1       0   402.9    .045       0  421.31      .1       0
     730     .05       0
#XS Ineff= 2 , 0
          229.06 2316.36
Permanent Ineff=
       F       F
Bank Sta=402.9,421.31
XS Rating Curve= 0 ,0
Exp/Cntr=0.3,0.1

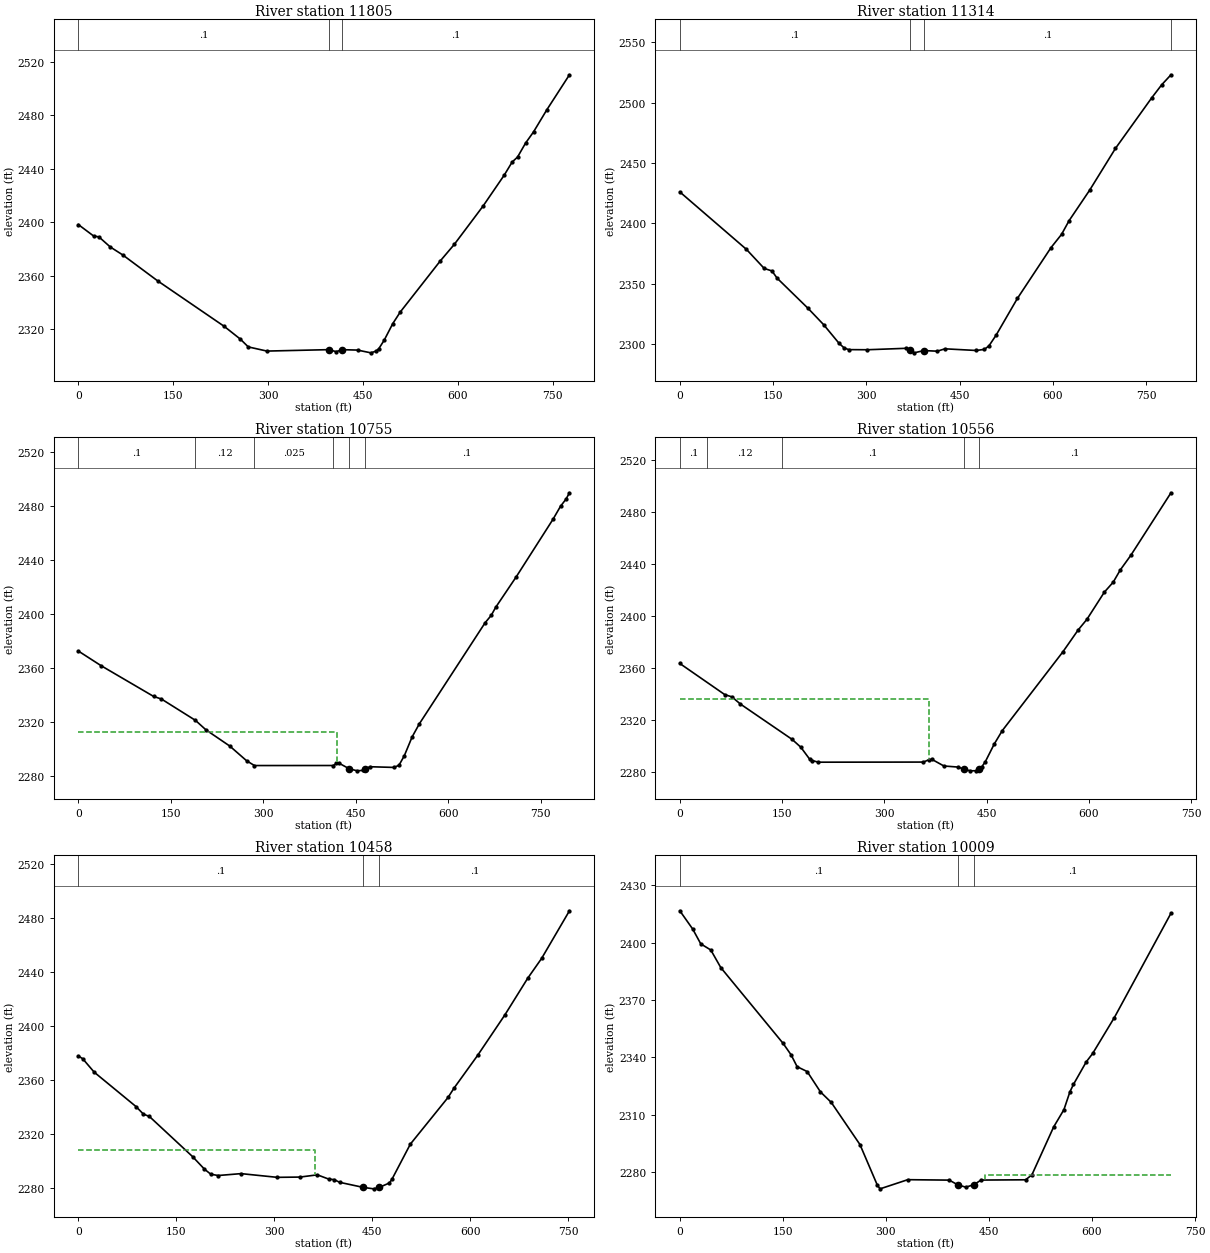
Type RM Length L Ch R = 1 ,11805   ,489.5,491.6,491.1
XS GIS Cut Line= 2
2231627.07002197462364.0575842122230890.24237346462609.412467047
#Sta/Elev= 30
       0 2398.29    24.1 2389.77    32.6 2389.06    50.6 2381.52    70.5 2375.52
   125.3 2356.29   230.7 2322.26   256.2 2312.73   268.8  2306.9   298.2  2303.8
     396 2304.86   407.8 2303.36   417.5 2304.84   441.5 2304.54   462.6 2302.48
     471  2303.8   475.2 2305.62   483.7 2311.94   497.3 2324.35   509.2 2333.03
   572.2 2371.02   594.6 2383.51   639.7 2411.88   673.4 2435.12     686 2444.96
   694.5 2448.66   707.1 2459.03   719.8 2467.46   740.8 2483.95   776.6 2510.11
#Mann= 3 ,-1,0
       0      .1       0     396    .045       0   417.5      .1       0
Bank Sta=396,417.5
XS Rating Curve= 0 ,0
Exp/Cntr=0.3,0.1

Type RM Length L Ch R = 1 ,11314   ,557.8,558.7,554.9
XS GIS Cut Line= 2
2231514.84389668461935.7279262922230754.26101481462149.186191839
#Sta/Elev= 30
       0 2426.02   107.2 2378.45   135.7 2362.71   148.2 2360.62   156.5 2354.64
   206.3 2329.65   231.3 2316.18   256.2 2300.68   264.5 2296.83   271.8 2295.51
   301.8 2295.41   364.2 2296.61   369.9 2294.99   376.7 2292.85   392.6 2294.71
   414.1 2294.23   426.5 2296.18     477  2294.8     490 2295.75   497.2 2298.61
   508.7 2307.46   542.9 2337.84     597 2379.91     614  2390.9   626.2 2402.32
   659.2 2427.48   700.7 2462.04   759.2 2504.02   775.1 2514.71     790 2522.96
#Mann= 4 ,-1,0
       0      .1       0   369.9    .045       0   392.6      .1       0
  789.97     .05       0
Bank Sta=369.9,392.6
XS Rating Curve= 0 ,0
Exp/Cntr=0.3,0.1

Type RM Length L Ch R = 1 ,10755   ,197.7,198.7,196.4
XS GIS Cut Line= 2
     2231423.738      461413.6352230670.97681854461673.409386497
#Sta/Elev= 30
       0 2372.59      37 2361.72     122 2339.03   134.9 2337.05     190 2321.28
   206.9  2314.3   245.6 2302.29     273 2291.38   285.6 2287.88   413.5 2287.91
   418.5 2289.48   422.7 2289.61   439.22285.519   452.3 2283.97   460.8 2284.31
   464.5 2285.63   473.5    2287   512.1 2286.49     520 2288.17   528.5 2295.07
   541.2 2309.03     553 2318.79   659.6  2393.5   669.4  2398.9   676.6 2404.81
   710.3 2427.64   769.7 2470.05   781.8  2479.6   790.8 2484.96   796.3 2489.59
#Mann= 6 ,-1,0
       0      .1       0     190     .12       0   285.6    .025       0
   413.5      .1       0   439.2    .045       0   464.5      .1       0
#XS Ineff= 2 , 0
          419.93 2312.37
Permanent Ineff=
       F       F
Bank Sta=439.2,464.5
XS Rating Curve= 0 ,0
Exp/Cntr=0.3,0.1

Type RM Length L Ch R = 1 ,10556   ,91.3,98.1,101.5
XS GIS Cut Line= 2
2231285.94257967461252.2413078182230612.97160722 461509.89977454
#Sta/Elev= 30
       0 2363.33    66.1 2339.34    76.4 2337.69    88.8 2332.17   164.7 2304.99
   177.5 2298.96   190.4 2289.81   194.6 2288.67   203.2 2287.44   357.4 2287.53
     366 2289.47   370.2 2289.51   387.4 2284.52   408.8 2283.66   416.5    2282
   426.4 2280.79   434.5 2280.89   438.9  2281.9   443.1 2283.97   448.1 2287.71
   461.3 2301.41     473 2311.64     562 2372.28   584.4 2389.09   597.3  2397.3
   622.9 2418.22   635.8 2425.81   646.3 2435.31   661.5 2446.35   720.6 2494.57
#Mann= 5 ,-1,0
       0      .1       0      40     .12       0     150      .1       0
   416.5    .045       0   438.9      .1       0
#XS Ineff= 2 , 0
          365.45 2336.08
Permanent Ineff=
       F       F
Bank Sta=416.5,438.9
XS Rating Curve= 0 ,0
Exp/Cntr(USF)=0,0
Exp/Cntr=0.3,0.1

Type RM Length L Ch R = 1 ,10458   ,449.7,449.5,436.4
XS GIS Cut Line= 4
2231270.17420258 461145.405684282230919.74630187461313.497116326
2230792.96547601461320.6196346332230583.56343778461430.306416561
#Sta/Elev= 30
       0 2377.62     6.7 2375.61    24.4 2365.58    88.3 2340.13    99.8 2334.45
   108.7 2332.82   175.2 2302.89   193.2 2293.67   202.9 2289.93   214.2 2288.98
   249.2 2290.38   304.7 2287.62   339.4 2287.83     366 2289.48   383.7 2286.28
   391.7 2285.95   400.2 2283.93   436.3 2280.17   452.2  2279.1   460.7 2280.16
   476.4 2283.45   480.4 2286.35   508.4 2312.25   566.2 2346.91   575.2 2353.73
   611.4 2378.04     653 2407.96   688.1 2435.25   709.3 2449.88     752 2485.26
#Mann= 3 ,-1,0
       0      .1       0   436.3    .045       0   460.7      .1       0
#XS Ineff= 2 , 0
          362.79 2307.73
Permanent Ineff=
       F       F
Bank Sta=436.3,460.7
XS Rating Curve= 0 ,0
Exp/Cntr(USF)=0,0
Exp/Cntr=0.3,0.1

Type RM Length L Ch R = 1 ,10009   ,412,414.2,414.2
XS GIS Cut Line= 2
 2231086.1887437460709.4736265372230469.90821236461071.710340948
#Sta/Elev= 30
       0 2416.71    18.8 2407.13    30.5 2399.41    45.1  2396.2    59.7 2386.97
   150.3 2347.39     162 2341.36   170.7  2335.2   185.4 2332.63   204.7    2322
   220.4 2316.52   262.2 2294.46   287.6 2273.14   291.5 2271.31   331.8  2276.1
   392.1 2275.87   404.5 2273.43   416.2 2272.18   427.9 2273.47   438.5  2275.9
   503.4 2276.04   512.5 2278.66   544.1 2303.66   559.1 2312.74   567.8 2322.05
     573 2325.95   591.5 2337.67   600.9 2342.09   632.5 2360.89   714.9 2415.43
#Mann= 3 ,-1,0
       0      .1       0   404.5    .045       0   427.9      .1       0
#XS Ineff= 2 , 0
                          443.76         2278.62
Permanent Ineff=
       F       F
Bank Sta=404.5,427.9
XS Rating Curve= 0 ,0
Exp/Cntr=0.3,0.1

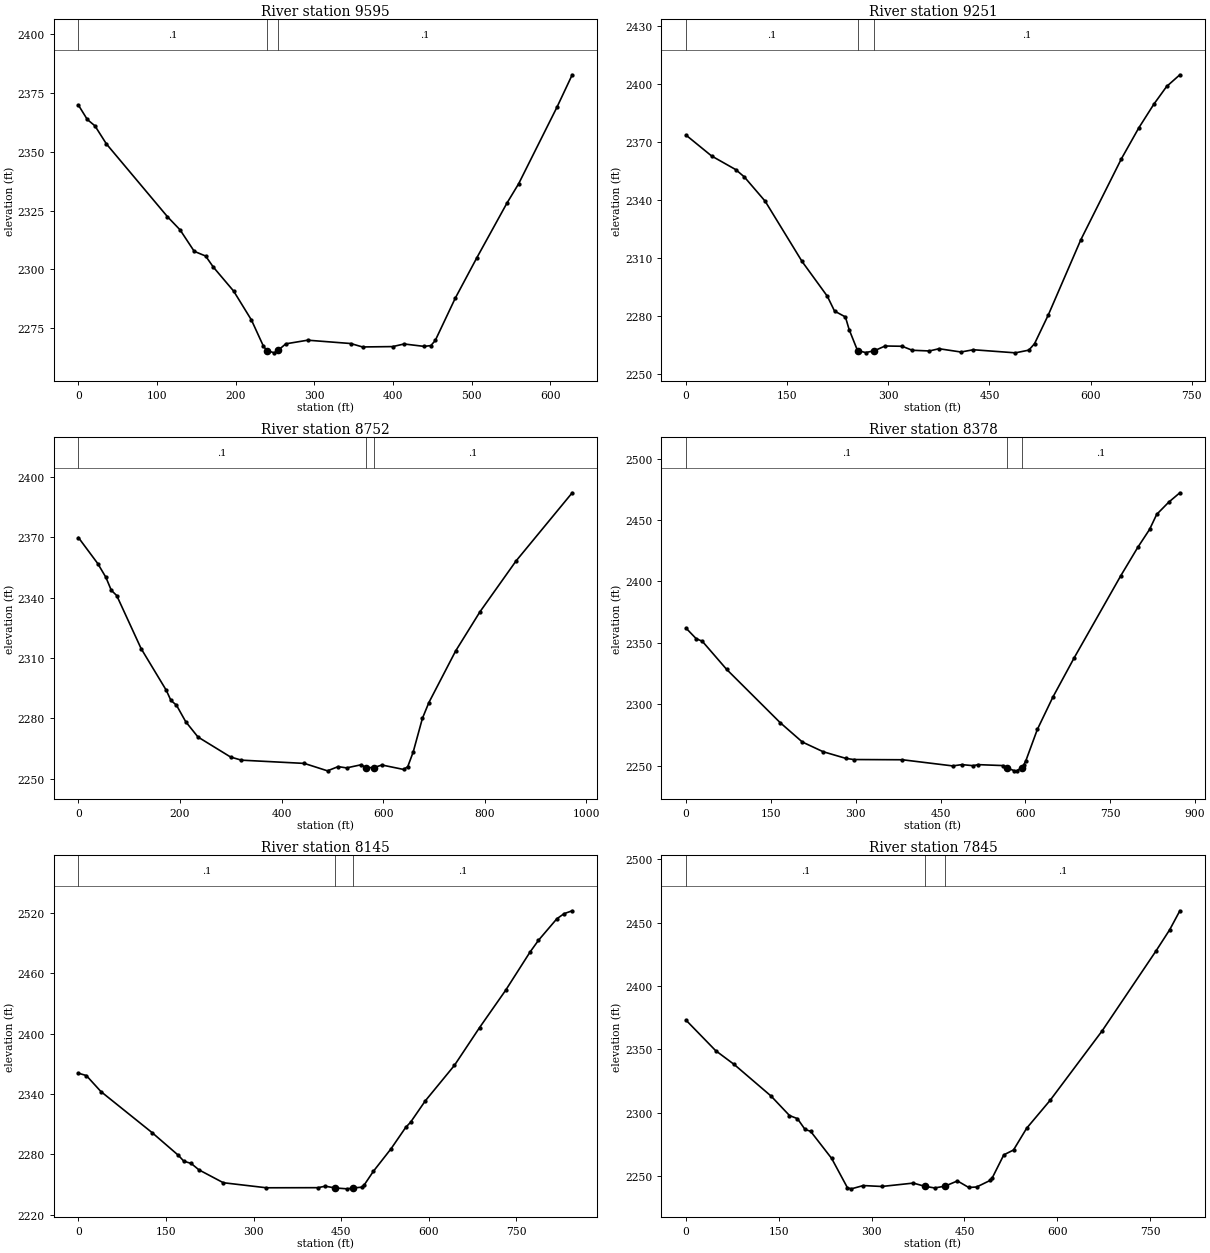
Type RM Length L Ch R = 1 ,9595    ,345.3,343.2,341.4
XS GIS Cut Line= 2
2230837.50934095 460391.907399532230320.03026042460747.969162749
#Sta/Elev= 30
       0 2369.87    11.3 2363.75      21 2361.06    35.6 2353.36   113.3 2322.39
   129.3 2316.81   147.3 2307.68   161.8 2305.68   171.6 2300.97   197.5 2290.74
   220.1 2278.45   235.1  2267.5   239.5 2265.49   249.2  2264.5   254.1 2265.61
   263.8 2268.33   291.6 2269.88   346.4 2268.46   361.4    2267   399.8 2267.16
   414.3 2268.27   439.8 2267.24   448.3 2267.59   453.9 2269.75   479.3 2287.72
   506.6 2304.83     545 2328.14   559.9 2336.38   608.8 2369.05   628.1 2382.77
#Mann= 3 ,-1,0
       0      .1       0   239.5    .045       0   254.1      .1       0
Bank Sta=239.5,254.1
XS Rating Curve= 0 ,0
Exp/Cntr=0.3,0.1

Type RM Length L Ch R = 1 ,9251    ,510.6,499,491.8
XS GIS Cut Line= 2
2230640.73906429 460076.182183072230093.53417826460562.783686767
#Sta/Elev= 30
       0 2373.67    37.9 2362.89    73.7 2355.83    86.4 2352.06   117.3 2339.49
     172 2308.32   209.5 2290.31   220.2 2282.63   236.3  2279.6   241.9 2273.02
   254.3 2262.19   266.4 2261.17   279.1 2262.08   295.2 2264.56   320.5 2264.42
   335.4 2262.35   360.9 2261.99   375.1 2263.15   407.6 2261.45   426.1 2262.62
   488.4 2261.02   508.3 2262.42   516.8 2265.74   537.2 2280.63   585.4 2319.51
   645.6 2361.43   671.4 2377.43   693.7 2389.67   712.7 2398.86   732.3 2404.91
#Mann= 3 ,-1,0
       0      .1       0   254.3    .045       0   279.1      .1       0
Bank Sta=254.3,279.1
XS Rating Curve= 0 ,0
Exp/Cntr=0.3,0.1

Type RM Length L Ch R = 1 ,8752    ,351.4,374.6,388.4
XS GIS Cut Line= 4
2230380.69970138459705.4286720862230080.71364531459970.190163624
2230008.06395857460228.0253263382230070.70779657460525.745897481
#Sta/Elev= 30
       0 2369.86      38 2356.96    54.1 2350.09    64.7 2343.67    75.4 2341.04
   123.4  2314.7   173.1 2293.91   182.1 2288.94   193.1 2286.55   211.2 2278.38
   235.4 2270.75   299.5 2260.82   320.8 2259.25   444.8 2257.63   490.4 2253.94
   511.3 2256.04   527.9  2255.4     557 2256.98   565.7 2255.53   581.9 2255.56
   597.5 2256.84   640.1 2254.64   648.4 2256.01   659.1 2263.28   677.3 2280.05
     690 2287.87   742.7 2313.51   790.6 2332.98   861.5 2358.19   972.2 2392.11
#Mann= 3 ,-1,0
       0      .1       0   565.7    .045       0   581.9      .1       0
Bank Sta=565.7,581.9
XS Rating Curve= 0 ,0
Exp/Cntr=0.3,0.1

Type RM Length L Ch R = 1 ,8378    ,235.8,232.3,229.5
XS GIS Cut Line= 4
2230289.62267416459619.7961659692230004.15422151459874.439386639
2229744.15009094459913.3059834782229529.71369458459989.698949678
#Sta/Elev= 30
       0  2361.9      18 2353.31    28.7 2351.26    71.6 2328.44   166.3 2285.05
   205.6 2269.24   242.4 2261.34   282.5 2255.93   296.5 2254.98   382.5  2254.8
   471.5 2249.79   487.7 2250.84   507.9 2249.97     516 2250.83   560.5 2250.07
   567.22248.317   580.7 2245.78   584.7 2245.83   593.2 2248.33   596.9 2250.37
   600.9 2254.12   621.1 2279.45   648.4 2305.62     686 2337.56   768.5 2404.46
   798.7 2427.67   819.5 2442.24   832.2 2454.54   853.5 2464.48   873.1  2472.1
#Mann= 3 ,-1,0
       0      .1       0   567.2    .045       0   593.2      .1       0
Bank Sta=567.2,593.2
XS Rating Curve= 0 ,0
Exp/Cntr(USF)=0,0
Exp/Cntr=0.3,0.1

Type RM Length L Ch R = 1 ,8145    ,298,300.3,298.1
XS GIS Cut Line= 2
     2230233.177      459541.2012229423.00567941459783.930992677
#Sta/Elev= 30
       0  2360.7    13.6 2358.33    38.6 2342.39   126.3 2301.51   171.1 2279.03
   180.6 2273.13   193.1 2270.89   206.4 2264.53   248.2  2251.7   322.1 2246.67
   410.3 2246.78   422.8 2248.25   439.5 2246.52   460.3 2245.62   469.9 2246.45
   485.4 2247.27   489.6 2249.55   505.2 2263.04   535.5 2285.51   560.6 2306.77
   568.9 2311.85     594 2333.06   644.1 2368.52   687.1 2406.08   731.8 2443.23
   773.5 2481.18     788 2492.93   819.5 2514.37     832 2519.47   845.8 2522.31
#Mann= 3 ,-1,0
       0      .1       0   439.5    .045       0   469.9      .1       0
Bank Sta=439.5,469.9
XS Rating Curve= 0 ,0
Exp/Cntr=0.3,0.1

Type RM Length L Ch R = 1 ,7845    ,179.5,180.6,181.4
XS GIS Cut Line= 2
2230153.18289741459263.3322431612229403.69437591459537.854201617
#Sta/Elev= 30
       0 2372.92    47.9 2348.88    77.8    2338   137.4 2313.09   167.2 2297.72
     180 2295.27   192.4 2286.71   201.3 2285.29   235.4 2263.84   260.9 2240.71
   267.2 2239.88   286.5 2242.47   316.3 2241.74   367.4 2244.42   385.7  2241.9
   401.9 2240.58   418.5    2242   438.7 2246.12   456.9 2240.97   469.7 2241.33
   491.7 2246.56   495.2 2248.77   513.6 2266.68   529.3 2270.52   550.6 2287.72
   588.4 2309.65   672.6 2364.53   759.9 2427.75   781.7 2444.24   798.2 2459.26
#Mann= 3 ,-1,0
       0      .1       0   385.7    .045       0   418.5      .1       0
Bank Sta=385.7,418.5
XS Rating Curve= 0 ,0
Exp/Cntr(USF)=0,0
Exp/Cntr=0.3,0.1

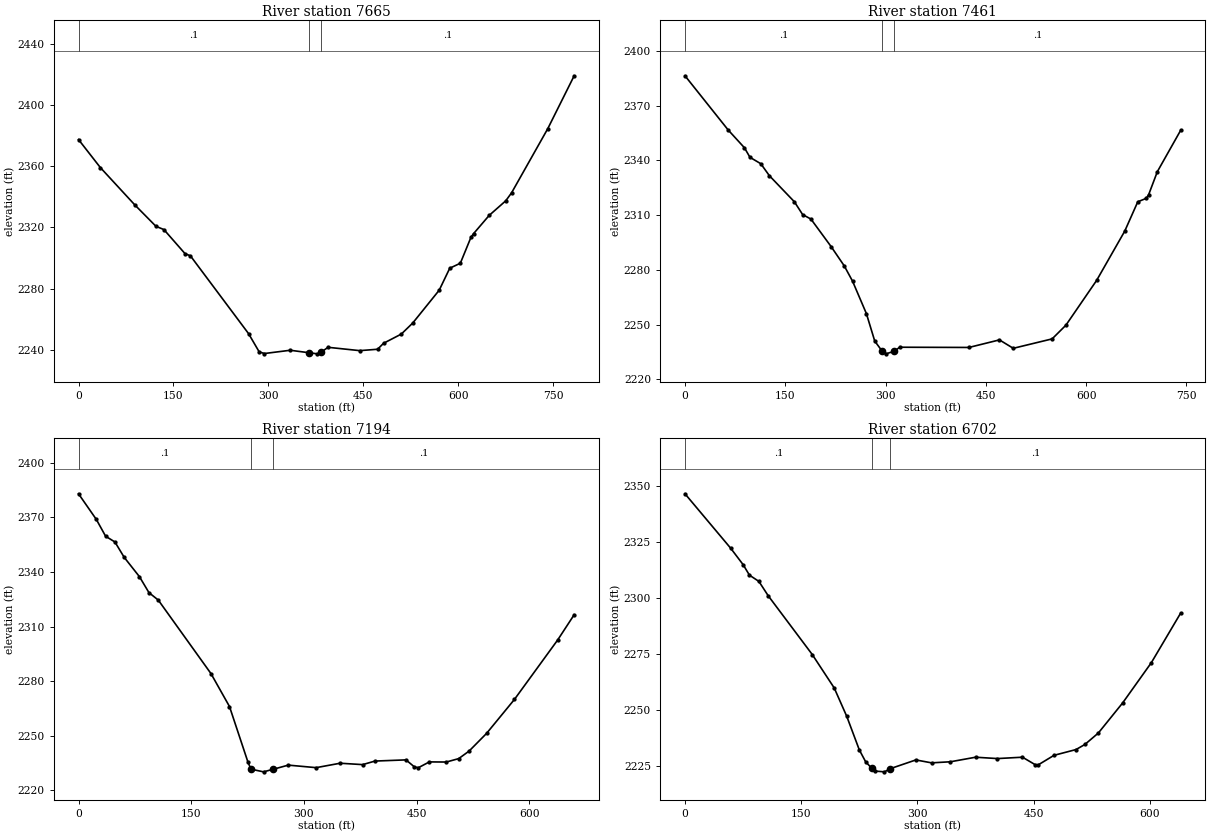
Type RM Length L Ch R = 1 ,7665    ,200.4,203.7,201.1
XS GIS Cut Line= 2
2230105.19684479459116.804371878 2229356.1585992459344.643043002
#Sta/Elev= 30
       0 2377.33    34.5 2359.02    88.9 2334.64   122.3 2320.65   134.9 2318.51
   168.3 2302.76   176.7 2301.39   268.6 2250.54   285.4 2238.61   293.7 2237.55
   334.5 2239.68   364.8 2238.02   377.4 2237.34   382.6 2238.23   394.1 2241.61
   444.2 2239.43   472.4 2240.34   481.9 2244.26   509.9 2250.26   527.9 2257.46
   569.7  2278.9   586.4 2293.28   603.1 2296.52   619.8 2313.38     624 2315.86
   648.7 2327.79   674.8  2337.3     684  2342.5   741.1 2384.35   782.9 2418.98
#Mann= 3 ,-1,0
       0      .1       0   364.8    .045       0   382.6      .1       0
Bank Sta=364.8,382.6
XS Rating Curve= 0 ,0
Exp/Cntr(USF)=0,0
Exp/Cntr=0.3,0.1

Type RM Length L Ch R = 1 ,7461    ,266.8,267.1,267.5
XS GIS Cut Line= 2
2230065.99714639458951.8368388062229350.62953764459146.345702248
#Sta/Elev= 30
       0 2386.31    64.5 2356.66    88.9 2346.88    97.2 2341.64   113.4 2338.13
   126.2 2331.58   163.6 2317.29     176 2310.26   188.4  2307.8   218.6 2292.71
   238.2 2282.17   250.6  2273.8   271.3 2256.04   283.8 2240.98   294.8 2235.48
   300.3 2233.97   312.8 2235.33   321.1 2237.59   424.7 2237.47   470.3 2241.61
     491    2237   549.1 2242.16   569.7 2249.66   615.6 2274.17   657.7 2301.19
   677.2 2317.27     690 2319.18   693.5 2321.21   706.5  2333.8   741.3  2356.4
#Mann= 3 ,-1,0
       0      .1       0   294.8    .045       0   312.8      .1       0
Bank Sta=294.8,312.8
XS Rating Curve= 0 ,0
Exp/Cntr=0.3,0.1

Type RM Length L Ch R = 1 ,7194    ,489,491.5,491.9
XS GIS Cut Line= 2
      2229943.19      458713.9052229302.89556515458873.584187267
#Sta/Elev= 30
       0 2382.98    23.7  2368.9    36.1 2359.64    48.5 2356.49    60.8 2348.07
    81.1 2337.44    93.8 2328.65   106.2 2324.57   176.3 2284.21     201 2266.09
   225.7 2235.39   229.6 2231.65   246.3 2230.19   258.7 2231.55   279.3 2233.88
   316.4 2232.49   348.3 2234.92   378.3 2234.16   394.7 2236.11     436 2236.76
   447.3 2232.86   452.5 2232.47   467.1 2235.65   489.6 2235.58   506.1 2237.44
   519.9 2241.56   543.2 2251.28   580.3 2269.94     638 2302.68   659.9 2316.52
#Mann= 3 ,-1,0
       0      .1       0   229.6    .045       0   258.7      .1       0
Bank Sta=229.6,258.7
XS Rating Curve= 0 ,0
Exp/Cntr=0.3,0.1

Type RM Length L Ch R = 1 ,6702    ,352,367.6,376.1
XS GIS Cut Line= 2
     2229850.323       458259.392229218.87134369458361.622651894
#Sta/Elev= 30
       0 2346.55    58.9  2322.3    75.1 2314.91    83.2 2310.25    95.4 2307.46
   107.5 2301.02   164.3 2274.83   192.6 2259.94   208.8 2247.26     225  2232.3
   233.1 2227.04   241.2 2224.03   245.3 2222.85   257.5 2222.51     265 2223.93
     298 2227.82   318.2 2226.52   342.6    2227     375 2229.03   403.3 2228.43
   435.6 2229.04     452  2225.7     456 2225.64   476.3 2229.88   504.6 2232.44
   516.1 2234.71   533.5 2239.83   564.9 2253.27   601.9 2271.21   639.7  2293.3
#Mann= 3 ,-1,0
       0      .1       0   241.2    .045       0     265      .1       0
Bank Sta=241.2,265
XS Rating Curve= 0 ,0
Exp/Cntr=0.3,0.1