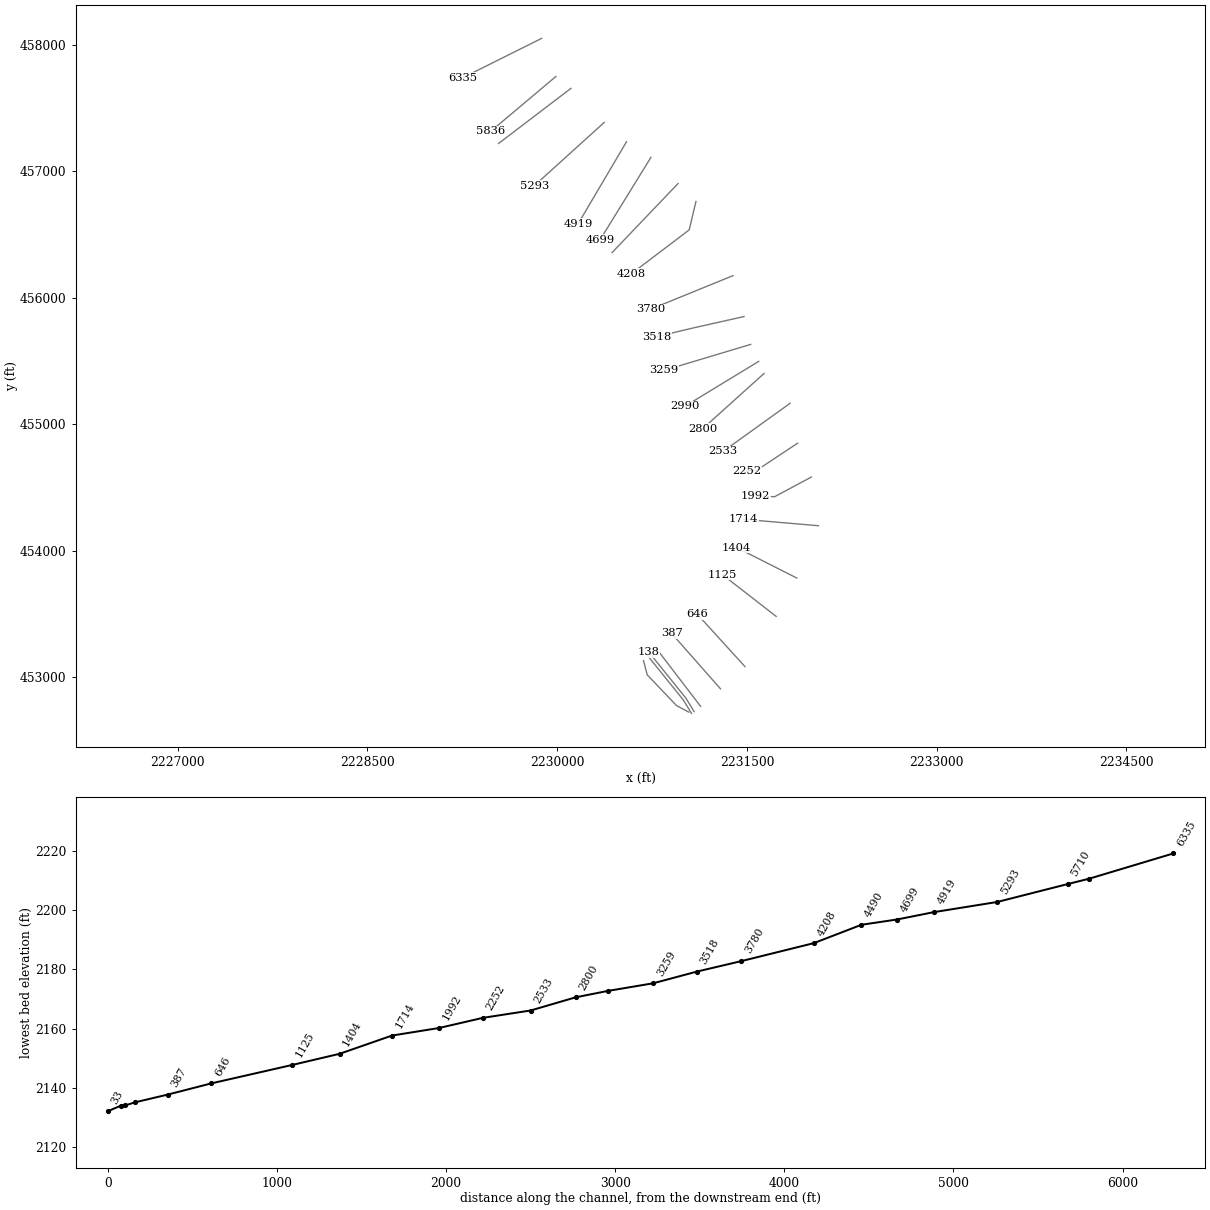
HEC-RAS study INDIANDRFT.prj: INDIANDRFT

--- INDIANDRFT.g01 (geometry) --- (continued)

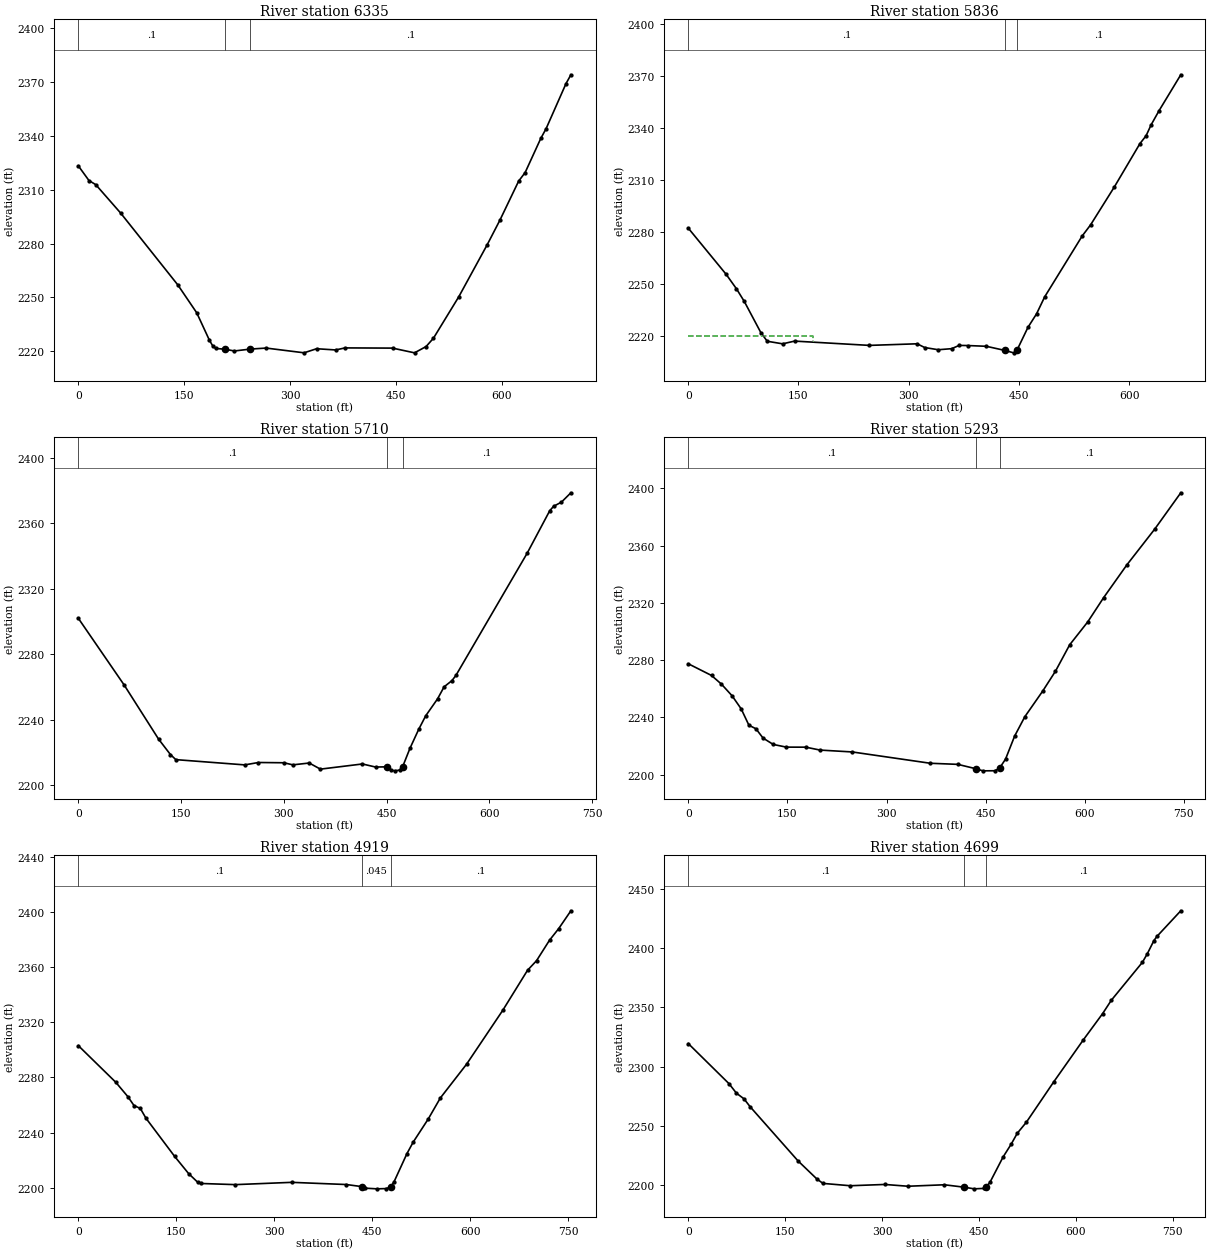
Type RM Length L Ch R = 1 ,6335    ,504.2,499.1,512.8
XS GIS Cut Line= 2
     2229878.229      458051.888 2229254.0442736457740.234223463
#Sta/Elev= 30
       0 2323.33      15 2315.17    24.7 2312.85    59.8 2297.07   140.9 2256.95
   167.7 2241.39   185.6 2226.16   190.1 2223.12   194.5 2221.55     208 2221.07
     221 2220.12   243.7 2221.18   266.1 2221.74   319.7  2219.1   337.5 2221.37
   364.4 2220.69   377.8 2221.83     445 2221.72   476.2 2219.08   492.6  2222.6
     503 2227.23   538.8 2250.29   579.1 2279.33   597.1 2293.02   623.7 2314.85
   632.9 2319.62     655 2338.61   662.6  2344.1   690.8 2369.24   697.7 2374.13
#Mann= 3 ,-1,0
       0      .1       0     208    .045       0   243.7      .1       0
Bank Sta=208,243.7
XS Rating Curve= 0 ,0
Exp/Cntr=0.3,0.1

Type RM Length L Ch R = 1 ,5836    ,127.1,126,126.3
XS GIS Cut Line= 2
2229990.39616016457750.3314681692229477.60131079457318.753391747
#Sta/Elev= 30
       0 2282.37    51.5  2255.8    65.6 2247.43    76.2 2240.18    98.9 2222.11
   107.5 2217.21   128.4 2215.73   144.7  2217.3   246.5 2214.83   311.4 2215.75
   321.8 2213.59   340.2 2212.33   358.4 2212.94   368.6 2214.81     380 2214.75
   405.6 2214.31   430.4 2211.97   442.8 2210.54   447.3 2212.06   462.3 2225.27
   473.9 2232.96     485 2242.79     536 2277.83   547.5 2284.27   579.5 2305.89
   614.6 2331.04     623 2335.58   629.8 2341.83   640.7 2350.07   670.2 2370.69
#Mann= 3 ,-1,0
       0      .1       0   430.4    .045       0   447.3      .1       0
#XS Ineff= 2 , 0
             170    2220
Permanent Ineff=
       F       F
Bank Sta=430.4,447.3
XS Rating Curve= 0 ,0
Exp/Cntr(USF)=0,0
Exp/Cntr=0.3,0.1

Type RM Length L Ch R = 1 ,5710    ,415.4,416.7,417.2
XS GIS Cut Line= 2
2230109.38306591457656.3624450792229537.21919884457220.760544783
#Sta/Elev= 30
       0 2301.84    66.9 2261.13   117.1 2228.13   134.4 2218.71   142.3 2215.59
   242.9 2212.38   262.9 2213.84     300 2213.68   313.2 2212.41   337.1 2213.52
   353.4 2209.79   414.7 2212.94   433.9 2211.07   451.3  2211.2     457 2209.07
   462.7 2208.75   469.1 2209.24  473.362211.164   484.1 2222.46   496.9 2234.07
   507.1 2242.32   524.4 2252.67     534 2260.04   545.4 2263.81   551.2 2266.97
   655.1 2341.48   688.2 2367.52   693.9 2370.25   705.3 2372.77   719.1 2378.48
#Mann= 3 ,-1,0
       0      .1       0   451.3    .045       0  473.36      .1       0
Bank Sta=451.3,473.36
XS Rating Curve= 0 ,0
Exp/Cntr=0.3,0.1

Type RM Length L Ch R = 1 ,5293    ,365.6,373.6,380.9
XS GIS Cut Line= 2
     2230372.094      457386.9142229819.51625469456886.789893057
#Sta/Elev= 30
       0 2277.49    35.2 2269.31    50.3 2263.22    66.3 2255.13    80.1 2245.98
    91.8 2234.55   102.4  2232.1   113.2 2225.59   128.6 2221.14   148.4 2219.27
   177.9 2219.23   199.4 2217.21   248.1  2215.9   366.2    2208   407.9 2207.23
     4352204.205   445.8 2202.71   463.9 2202.77     4712204.563   480.1 2210.88
   493.9    2227   509.3  2240.5   536.4 2258.43   555.6 2272.23   577.2 2290.74
   604.6 2306.77   628.5 2323.62   663.8 2346.59     706 2371.59   745.3 2396.87
#Mann= 3 ,-1,0
       0      .1       0     435    .045       0     471      .1       0
Bank Sta=435,471
XS Rating Curve= 0 ,0
Exp/Cntr=0.3,0.1

Type RM Length L Ch R = 1 ,4919    ,220.7,220.2,219.9
XS GIS Cut Line= 2
2230548.67092761457234.5858908622230165.47944269456585.012221263
#Sta/Elev= 30
       0 2303.06    57.4 2276.49    75.9 2266.05    85.2 2259.67    94.9 2257.56
   103.6 2250.42   147.4 2222.82   168.8 2210.37   182.8 2204.04   187.4 2203.18
   240.4 2202.34   326.7    2204   410.4 2202.41     434 2200.91   439.5 2199.77
   457.1 2199.29   471.7 2199.48   478.2 2200.71   483.4 2204.41   503.2 2224.86
   512.7 2233.15   535.7 2249.87   554.3 2265.15   594.4  2289.6   649.9  2328.7
   687.8 2357.71   701.6 2364.66   721.5 2379.52   735.4 2387.83   754.2 2400.83
#Mann= 3 ,-1,0
       0      .1       0     434    .045       0   478.2      .1       0
Bank Sta=434,478.2
XS Rating Curve= 0 ,0
Exp/Cntr(USF)=0,0
Exp/Cntr=0.3,0.1

Type RM Length L Ch R = 1 ,4699    ,215.2,209.2,205.7
XS GIS Cut Line= 2
2230741.38170138457110.7303718512230340.94090642456461.683190393
#Sta/Elev= 30
       0 2319.44      63 2285.61    74.7 2277.48    86.3 2272.77    95.8  2266.1
   169.9 2220.42   199.2 2205.09   208.6 2201.38   250.9 2199.41   304.3 2200.49
   340.2 2198.98   396.6 2200.22   427.12198.183   442.8 2196.79   457.7 2197.16
   461.3 2198.37   467.1 2202.24   487.4 2223.62     500  2234.5   509.4 2243.67
   523.5 2253.01   565.8 2287.01   611.7 2322.54   641.5 2344.63   655.1    2356
   703.2 2388.02   710.8 2395.24   720.9 2406.23   725.6 2409.82   762.6 2431.49
#Mann= 3 ,-1,0
       0      .1       0   427.1    .045       0   461.3      .1       0
Bank Sta=427.1,461.3
XS Rating Curve= 0 ,0
Exp/Cntr=0.3,0.1

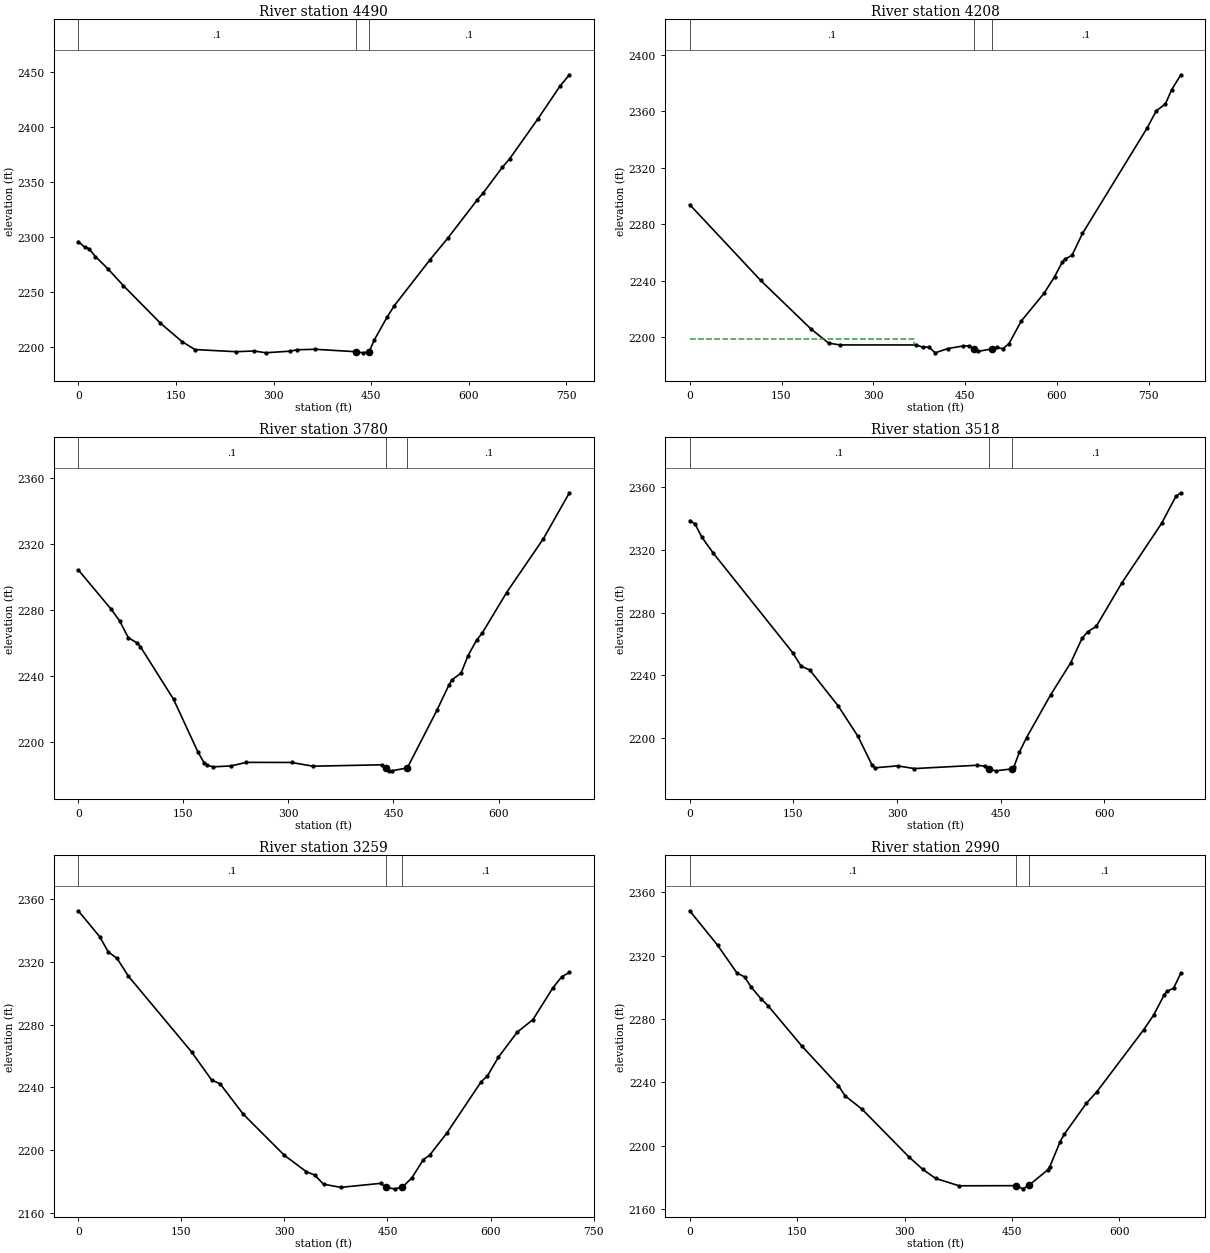
Type RM Length L Ch R = 1 ,4490    ,283.6,282.1,278.3
XS GIS Cut Line= 2
2230956.00986909456904.2764963762230434.72478631456358.783128015
#Sta/Elev= 30
       0 2295.95     9.8 2290.86    16.2 2289.57    26.4 2282.34    46.1 2270.85
    69.2 2255.99     126 2222.03   159.2 2205.28   179.2    2198   242.2 2196.06
   269.9  2196.7   287.8  2195.1   325.2 2196.52   336.2  2197.8   363.9 2198.24
   426.4 2196.04   437.8 2195.02   446.9 2196.18   454.7 2206.62   474.5 2227.53
   485.6 2237.87   539.6  2278.9   567.9 2299.19   612.9 2333.74   621.7 2339.72
   651.6  2363.4   662.7    2371   706.1 2407.16   740.1 2436.92   754.5 2447.14
#Mann= 3 ,-1,0
       0      .1       0   426.4    .045       0   446.9      .1       0
Bank Sta=426.4,446.9
XS Rating Curve= 0 ,0
Exp/Cntr(USF)=0,0
Exp/Cntr=0.3,0.1

Type RM Length L Ch R = 1 ,4208    ,427.5,428.2,419.3
XS GIS Cut Line= 3
2231097.36427674456762.0431549852231043.95559575456537.645841784
2230588.08775288456192.050103323
#Sta/Elev= 30
       0 2293.85     116 2240.12   198.3 2205.68     227 2195.74   245.4 2194.42
   370.5 2194.41     381 2192.75     391 2192.99   401.1 2188.82   422.1 2191.87
   446.2 2193.64   456.4 2193.83     465 2191.38   471.3 2189.88   493.5 2191.58
   501.4 2192.72   511.5  2191.7   521.5 2195.15     542 2211.43   579.2 2231.07
   596.3 2242.78   608.8 2253.02   613.4 2255.27   624.8 2257.95   641.9 2273.41
   747.4 2348.04   762.5 2360.31   777.5 2365.22   787.6 2375.26   802.7 2385.88
#Mann= 3 ,-1,0
       0      .1       0     465    .045       0   493.5      .1       0
#XS Ineff= 2 , 0
          366.94 2198.64
Permanent Ineff=
       F       F
Bank Sta=465,493.5
XS Rating Curve= 0 ,0
Exp/Cntr=0.3,0.1

Type RM Length L Ch R = 1 ,3780    ,264.3,261.2,257.9
XS GIS Cut Line= 2
     2231390.343      456176.2262230741.05774714455911.520023371
#Sta/Elev= 30
       0 2304.48      47 2280.62    59.2 2273.46    71.5 2263.33    84.4 2260.18
    88.7 2257.96     136 2226.11   170.8 2194.21   179.4 2187.81   183.8 2186.19
   192.4 2185.19   218.3 2185.75   239.9  2187.9   304.7 2187.84     335 2185.58
   433.6 2186.43   439.7 2184.54   442.9 2182.84   447.3 2182.77  469.72 2184.54
   512.1 2219.49   529.3 2234.91   533.7 2237.95   546.6 2242.02   556.4  2252.5
   568.6 2261.87   576.9 2266.31   611.4  2290.7   663.8 2323.21   701.2 2351.17
#Mann= 3 ,-1,0
       0      .1       0   439.7    .045       0  469.72      .1       0
Bank Sta=439.7,469.72
XS Rating Curve= 0 ,0
Exp/Cntr=0.3,0.1

Type RM Length L Ch R = 1 ,3518    ,258.8,259.5,260.4
XS GIS Cut Line= 3
2231477.44731484455852.8173393022231077.16178599455763.073608634
 2230785.1385354455693.272929225
#Sta/Elev= 30
       0 2338.59     7.5 2336.58    17.7 2327.96    34.1 2317.87   148.9 2254.56
   161.2 2245.86   173.5 2243.56   214.5 2220.77   243.2 2201.35   263.7 2183.02
   267.8 2181.21   300.6 2182.42   325.1  2180.7   415.3 2182.81   427.7  2182.2
   432.5 2180.33   442.5 2179.26   465.7 2180.47   468.8 2181.59     477 2191.24
   487.2 2200.38   522.3 2227.78   551.1 2248.02   567.5 2263.57   575.7 2267.79
   588.1 2271.25     625 2298.82   682.7 2336.89   703.2 2353.96   710.5 2356.32
#Mann= 3 ,-1,0
       0      .1       0   432.5    .045       0   465.7      .1       0
Bank Sta=432.5,465.7
XS Rating Curve= 0 ,0
Exp/Cntr(USF)=0,0
Exp/Cntr=0.3,0.1

Type RM Length L Ch R = 1 ,3259    ,264.4,268.5,273.9
XS GIS Cut Line= 2
2231529.99030997455632.6552250742230845.27383576455427.349444963
#Sta/Elev= 30
       0 2352.76    31.1 2336.25    43.7 2326.45    56.2 2322.49    72.9 2311.05
   164.8 2262.73     194 2244.81   206.5 2242.29   239.9 2223.05   299.8 2196.76
   331.9 2186.26   344.3 2184.01   356.9 2178.26   381.9 2176.25   440.4 2178.81
   447.6 2176.24   460.4  2175.3   471.7 2176.36   485.6 2182.36   502.2 2193.98
   511.4 2196.78   536.4  2210.9   586.5 2243.74   595.4 2247.31   611.4 2259.29
   638.8 2275.28   661.7 2283.32   690.9 2303.69   703.5 2310.61   714.8 2313.41
#Mann= 3 ,-1,0
       0      .1       0   447.6    .045       0   471.7      .1       0
Bank Sta=447.6,471.7
XS Rating Curve= 0 ,0
Exp/Cntr=0.3,0.1

Type RM Length L Ch R = 1 ,2990    ,187,190.6,195.2
XS GIS Cut Line= 2
2231593.49472265455498.5820471382231007.65421166455141.913306286
#Sta/Elev= 30
       0 2348.39      39 2326.58      66 2309.07    76.5 2306.65    85.8 2300.19
    99.9 2292.58   109.3 2288.44   156.5 2262.98   207.6 2237.94     217 2231.47
   240.7 2223.03   305.9 2192.98   325.1 2185.16   343.4  2179.3   376.2 2174.64
   456.1 2174.73   465.2 2172.72   473.5 2174.87   499.7 2184.59   502.7 2186.54
   517.2 2202.38     523 2207.18   554.1 2226.85   568.2 2233.83   633.8  2273.1
   647.8 2282.44   662.7  2295.3   666.5  2297.5   675.9 2299.58   685.9 2309.09
#Mann= 3 ,-1,0
       0      .1       0   456.1    .045       0   473.5      .1       0
Bank Sta=456.1,473.5
XS Rating Curve= 0 ,0
Exp/Cntr(USF)=0,0
Exp/Cntr=0.3,0.1

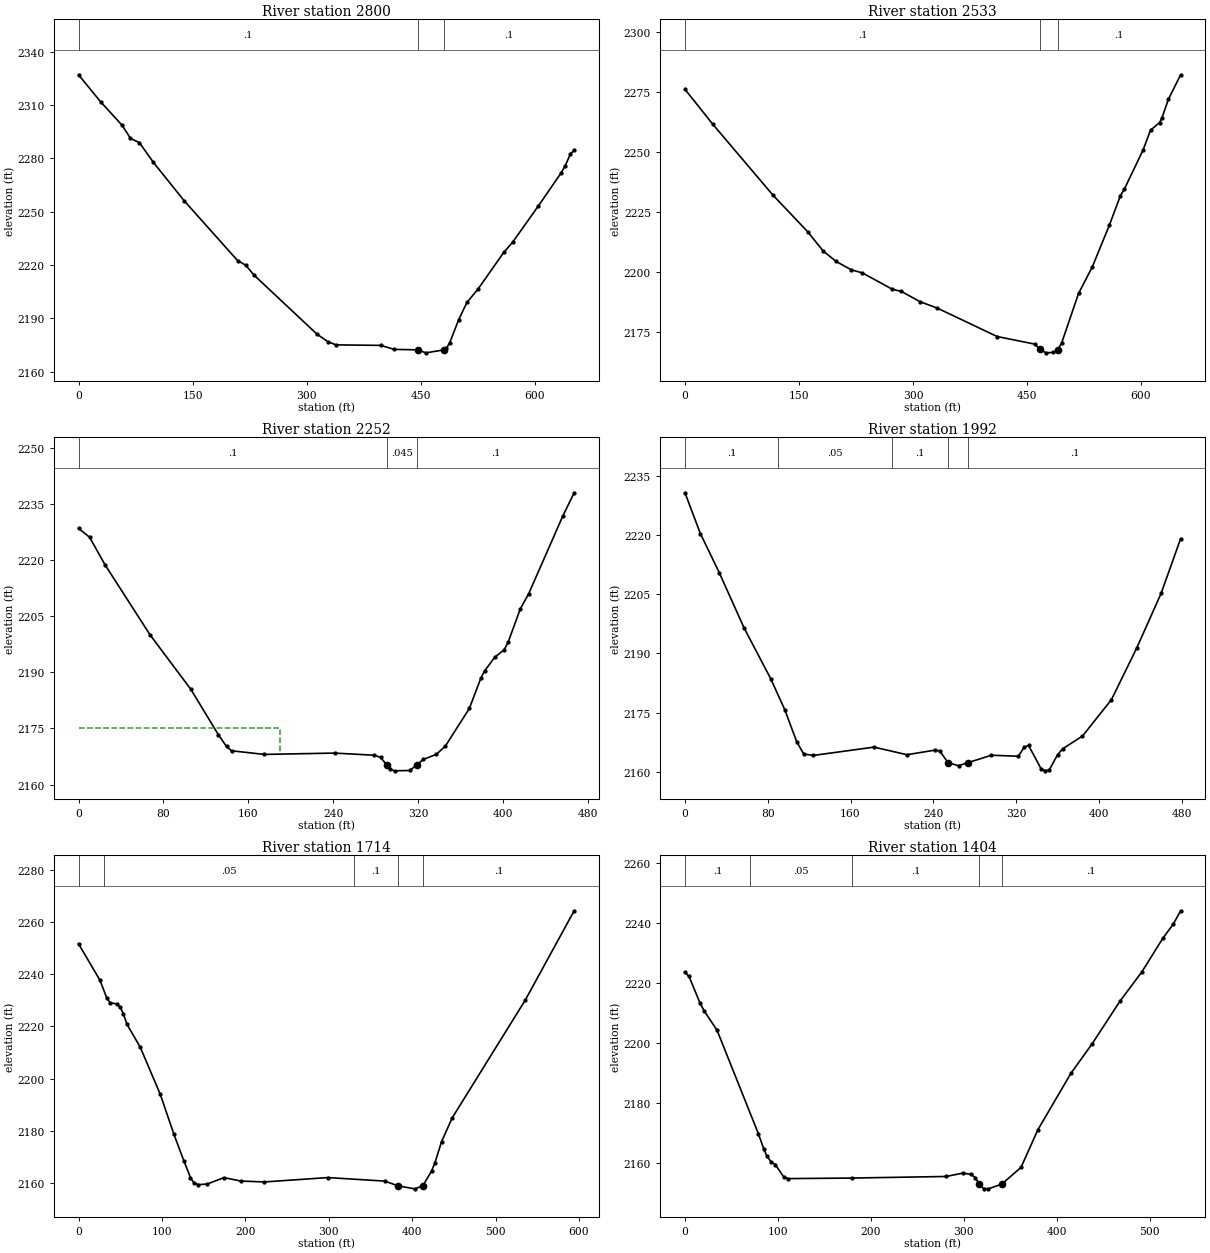
Type RM Length L Ch R = 1 ,2800    ,267.9,266.4,263.2
XS GIS Cut Line= 2
     2231635.593      455402.903 2231151.4085961454967.061720198
#Sta/Elev= 30
       0 2327.05    29.1 2311.82    57.5 2298.53    68.3 2291.23    80.1 2288.85
    98.2 2277.87   139.1 2256.04   209.1 2222.47   219.9 2219.87   230.6 2214.35
   313.5 2181.05   327.5 2176.93   338.3 2175.05   397.3 2174.75   415.1  2172.5
445.59052172.247   456.7 2170.56480.78972172.258   483.6 2173.16     488 2176.33
   499.7 2189.22   510.6 2198.96   524.8 2206.25   558.9 2227.05   570.6 2232.81
   604.1 2253.01   634.3 2271.82   639.7 2275.82   646.6 2282.52   651.5 2284.55
#Mann= 3 ,-1,0
       0      .1       0445.5905    .045       0480.7897      .1       0
Bank Sta=445.5905,480.7897
XS Rating Curve= 0 ,0
Exp/Cntr=0.3,0.1

Type RM Length L Ch R = 1 ,2533    ,283,281.4,280.9
XS GIS Cut Line= 2
2231841.76010694455167.3140296152231312.07506607454786.854733616
#Sta/Elev= 30
       0 2275.98    36.4  2261.5   115.2 2232.07   161.4 2216.63   181.9 2208.56
   198.9 2204.22   218.6 2200.77   233.4 2199.45   272.8 2192.64   284.8 2191.71
   309.3 2187.44   331.9 2184.79   410.7 2172.93     460 2169.77467.19852167.655
   474.7 2166.12   484.6 2166.29   490.5 2167.42   495.7 2170.27   517.9  2190.9
   535.8 2201.82   558.5 2219.41     573 2231.69   578.2 2234.42   602.8 2250.69
   612.6 2258.94   624.6 2262.15   627.5    2264   636.1 2271.83   652.2 2282.05
#Mann= 3 ,-1,0
       0      .1       0467.1985    .045       0   490.5      .1       0
Bank Sta=467.1985,490.5
XS Rating Curve= 0 ,0
Exp/Cntr=0.3,0.1

Type RM Length L Ch R = 1 ,2252    ,261.4,259.8,258.3
XS GIS Cut Line= 3
2231900.52490228454851.3912653362231580.01157846454639.140219787
 2231497.3903661454633.442205141
#Sta/Elev= 30
       0 2228.44    10.5 2226.04    24.9 2218.73    67.6 2199.91     106 2185.38
   131.7 2173.35   139.5 2170.16   144.3 2169.01     175 2168.04   241.4 2168.39
   278.7 2167.82   284.7 2167.25   290.5 2165.23   293.4 2164.02   297.9 2163.65
   312.3 2163.75  318.712165.227   325.1  2166.7   337.3 2168.06   345.8 2170.26
   368.4 2180.32   379.4 2188.52   382.8 2190.34   392.3 2193.99   401.1 2195.97
   404.9 2197.96   416.3 2206.82   424.4 2211.01   456.4 2231.66   467.2 2237.93
#Mann= 3 ,-1,0
       0      .1       0   290.5    .045       0  318.71      .1       0
#XS Ineff= 2 , 0
             190    2175
Permanent Ineff=
       F       F
Bank Sta=290.5,318.71
XS Rating Curve= 0 ,0
Exp/Cntr(USF)=0,0
Exp/Cntr=0.3,0.1

Type RM Length L Ch R = 1 ,1992    ,287.3,278.3,267
XS GIS Cut Line= 3
2232009.35532668454584.0787237662231718.85540911454428.717271984
2231569.28252466 454434.41528663
#Sta/Elev= 30
       0 2230.78    14.9 2220.41    33.1 2210.53      57 2196.55      83 2183.54
    96.6 2175.65   107.9 2167.66   114.7 2164.52   123.8 2164.12   182.8 2166.24
   214.5 2164.31   241.8 2165.48   246.3 2165.27   254.2 2162.31   264.4 2161.52
  273.59  2162.3   296.2 2164.18   322.2 2163.92   327.9 2166.21   332.1 2166.67
   344.1 2160.81   348.1 2160.22   352.1 2160.46   360.1 2164.28     365  2165.8
   384.2 2169.04   412.2 2178.27   436.6 2191.36   460.2 2205.24   479.1 2219.13
#Mann= 5 ,-1,0
       0      .1       0      90     .05       0     200      .1       0
   254.2    .045       0  273.59      .1       0
Bank Sta=254.2,273.59
XS Rating Curve= 0 ,0
Exp/Cntr(USF)=0,0
Exp/Cntr=0.3,0.1

Type RM Length L Ch R = 1 ,1714    ,316.1,309.7,302.3
XS GIS Cut Line= 2
2232065.92461483454199.4926124072231473.84696133454250.297955612
#Sta/Elev= 30
       0 2251.74    25.8 2237.72    33.9 2230.88    37.9 2229.16    45.9 2228.64
    49.9 2227.46    53.9 2224.81      58 2220.89      74 2212.05    98.1  2193.9
   114.2 2178.79   126.2 2168.51   134.2 2162.01   138.3    2160   143.7 2159.29
   154.3 2159.51   174.4 2161.98   194.5 2160.67   222.6 2160.31     299    2162
   367.1 2160.64   383.2 2158.81   403.2 2157.67   412.9 2158.84   423.3 2164.52
   427.3 2167.62   435.3 2175.78     448 2184.88   535.7 2230.14   594.3 2264.42
#Mann= 5 ,-1,0
       0      .1       0      30     .05       0     330      .1       0
   383.2    .045       0   412.9      .1       0
Bank Sta=383.2,412.9
XS Rating Curve= 0 ,0
Exp/Cntr(USF)=0,0
Exp/Cntr=0.3,0.1

Type RM Length L Ch R = 1 ,1404    ,282.7,279.4,275.8
XS GIS Cut Line= 2
2231894.82688763453785.8625266072231419.04266473454026.603645384
#Sta/Elev= 30
       0 2223.57     4.4 2222.13    16.3 2213.19    20.9 2210.56    34.4 2204.32
    78.9  2169.9    84.8 2164.78    88.1 2162.39    92.6 2160.53    97.1 2159.61
   106.1 2155.54   110.6 2154.92     180 2155.11   280.9 2155.63   299.1 2156.76
   307.8 2156.31   312.3 2155.28   316.1 2153.26   321.3 2151.62   326.3 2151.52
   340.8  2153.1   361.5 2158.65   379.6 2171.15   415.2 2189.94   437.8 2199.66
     468 2213.95   491.6 2223.71     514 2234.83   525.4 2239.59   533.2 2243.98
#Mann= 5 ,-1,0
       0      .1       0      70     .05       0     180      .1       0
   316.1    .045       0   340.8      .1       0
Bank Sta=316.1,340.8
XS Rating Curve= 0 ,0
Exp/Cntr(USF)=0,0
Exp/Cntr=0.3,0.1

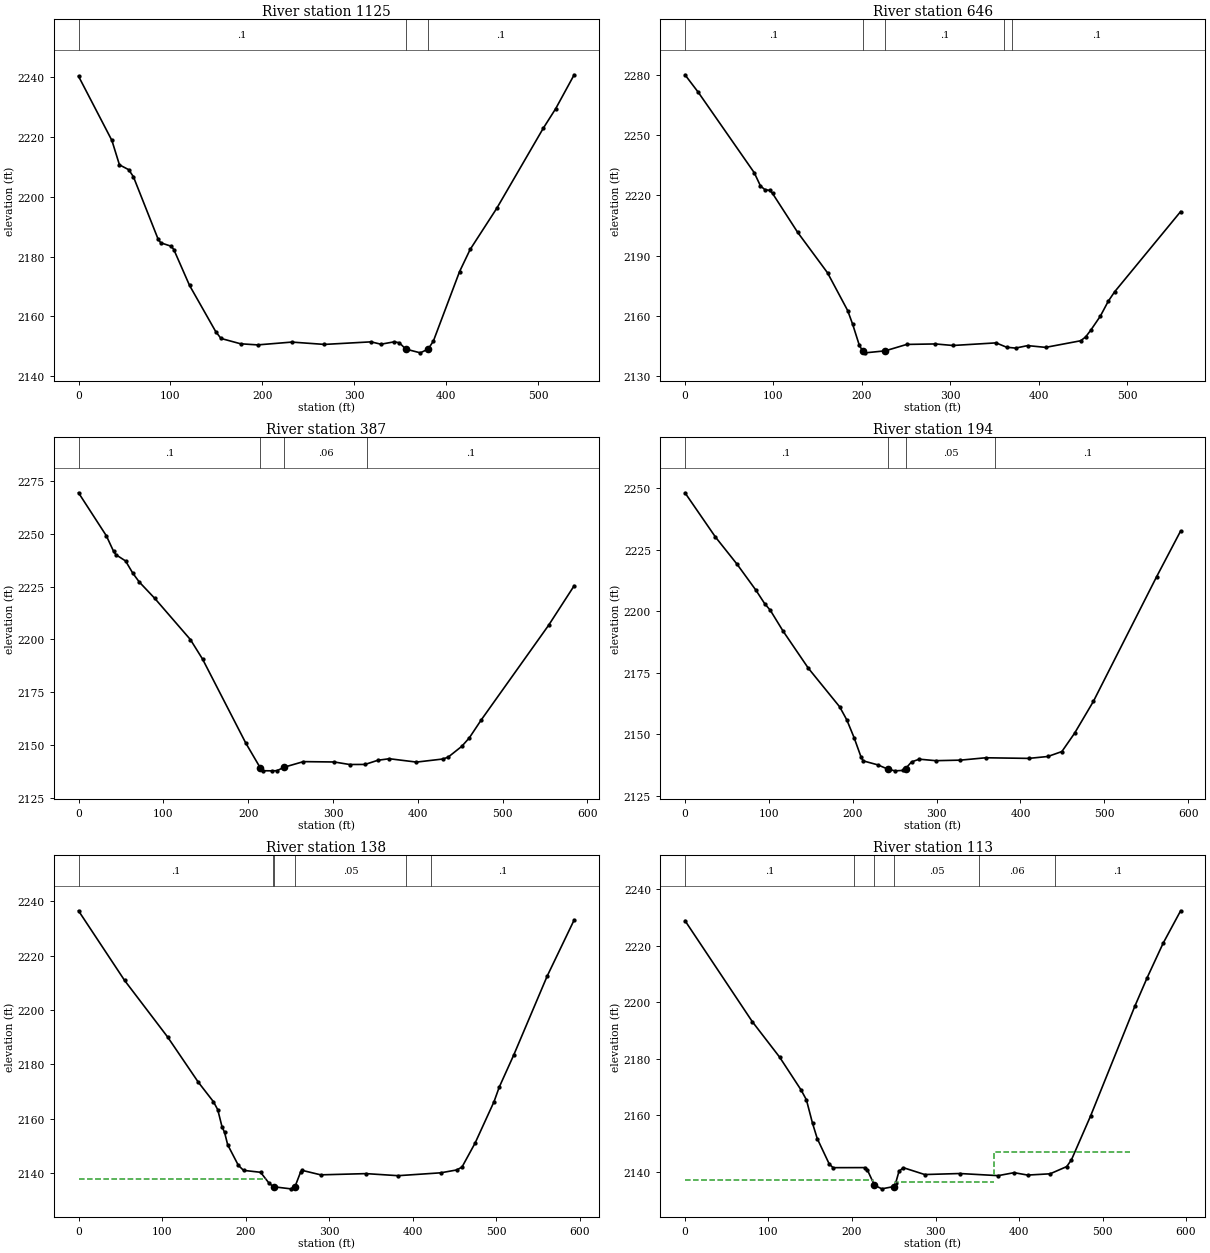
Type RM Length L Ch R = 1 ,1125    ,480.6,478.9,474.4
XS GIS Cut Line= 2
2231731.32552294453482.9180812822231305.73307102453813.543622447
#Sta/Elev= 30
       0 2240.38    36.3 2218.87    44.5 2210.71    54.6 2209.08    59.7 2206.72
    86.5 2185.87    89.4 2184.61   100.8 2183.45   103.6 2182.36   120.7 2170.35
   149.2 2154.87   154.9 2152.59   176.2  2150.8   194.8 2150.43   231.9 2151.37
   267.4 2150.59     318 2151.45   328.8 2150.66   343.4 2151.46   348.8 2151.14
   355.8 2149.03   371.6 2147.77   380.1 2149.03   385.8 2151.69   414.3 2174.97
   425.8 2182.38   454.8 2196.19   505.4 2223.01   518.8 2229.51   538.9 2240.86
#Mann= 3 ,-1,0
       0      .1       0   355.8    .045       0   380.1      .1       0
Bank Sta=355.8,380.1
XS Rating Curve= 0 ,0
Exp/Cntr(USF)=0,0
Exp/Cntr=0.3,0.1

Type RM Length L Ch R = 1 ,646     ,259.1,258.7,258.6
XS GIS Cut Line= 2
2231484.87758296453086.0856998632231107.74561225 453500.34465215
#Sta/Elev= 30
       0 2279.98      15 2271.28    78.3 2231.22    85.3 2224.66    90.2 2222.83
    96.1 2222.38      99 2220.89   127.3 2201.57   161.1  2181.4   183.9 2162.58
   189.6 2155.67   197.1 2145.23   200.9 2142.47   203.7 2141.55   226.4 2142.55
   250.6 2145.74     283 2145.98   302.8 2145.21   351.6 2146.51   363.5 2144.35
   373.6 2143.91   387.3 2145.15   407.6 2144.27   447.2 2147.56   452.9 2149.49
   458.6 2152.81   469.4 2159.78   478.4 2167.24   485.6 2171.94   560.2 2211.88
#Mann= 5 ,-1,0
       0      .1       0   200.9    .045       0   226.4      .1       0
     360     .05       0     370      .1       0
Bank Sta=200.9,226.4
XS Rating Curve= 0 ,0
Exp/Cntr(USF)=0,0
Exp/Cntr=0.3,0.1

Type RM Length L Ch R = 1 ,387     ,194.2,193,191.8
XS GIS Cut Line= 2
2231291.54929551452910.2473236462230905.06159543453348.619673878
#Sta/Elev= 30
       0 2269.36    32.8 2249.02    41.3 2241.69    44.1 2240.05    55.5 2237.09
      64 2231.31    71.6 2227.15    89.8 2219.43   131.9 2199.89   146.2 2190.69
   197.2 2150.91   214.2 2139.25   217.2 2137.81   227.9 2137.76     234 2137.83
   242.5 2139.49   265.2 2142.12   301.5 2141.95   319.6 2140.76   337.8 2140.79
   353.1 2142.78   366.5 2143.49   398.5  2141.9   429.6 2143.36   435.8 2144.24
   451.8 2149.33   460.7 2153.33   474.9  2161.9   554.3 2206.68   584.4 2225.36
#Mann= 4 ,-1,0
       0      .1       0   214.2    .045       0   242.5     .06       0
     340      .1       0
Bank Sta=214.2,242.5
XS Rating Curve= 0 ,0
Exp/Cntr(USF)=0,0
Exp/Cntr=0.3,0.1

Type RM Length L Ch R = 1 ,194     ,57,56.3,57.1
BEGIN DESCRIPTION:
structure xs 4
END DESCRIPTION:
XS GIS Cut Line= 2
2231133.90840846452772.3223278882230774.73515214453241.686911086
#Sta/Elev= 30
       0 2248.16    36.3 2230.19    62.1 2219.13    84.6 2208.57      95 2203.12
   101.7 2200.43   116.9 2191.98   147.1 2176.86   184.5 2161.15     193 2155.83
   201.6 2148.69   210.1 2140.62   212.6  2139.2   230.1 2137.57   241.5 2135.91
   250.1 2135.16   259.6 2135.32     263 2136.06   270.1 2138.77   279.3  2139.9
     299 2139.29   328.5 2139.51   358.5 2140.47   409.9 2140.22   432.7 2140.99
   449.4    2143   464.5 2150.42   486.9 2163.34   562.3 2214.01     591 2232.64
#Mann= 4 ,-1,0
       0      .1       0   241.5    .045       0     263     .05       0
     370      .1       0
Bank Sta=241.5,263
XS Rating Curve= 0 ,0
Exp/Cntr(USF)=0,0
Exp/Cntr=0.5,0.3

Type RM Length L Ch R = 1 ,138     ,25.2,24.9,25.7
BEGIN DESCRIPTION:
structure xs 3; 9 ft between structure and xs
END DESCRIPTION:
XS GIS Cut Line= 3
2231082.91935403452730.0326603412231019.32289746452834.860818506
2230723.94443136453201.543372265
#Sta/Elev= 30
       0 2236.46    55.1 2210.86   106.6 2190.05   143.5 2173.35   161.5 2166.22
   166.7 2163.28   171.8 2157.01   174.9  2154.9   178.6 2150.36   191.4 2142.77
   197.6 2140.93     218 2140.22   228.3 2136.15   233.5  2134.9     254 2134.13
   259.1 2134.84   265.9 2140.28   267.9 2140.92     290 2139.28   344.4 2139.73
   382.7 2138.97   433.8 2140.03   452.8 2141.08   459.2 2142.15   474.9 2150.99
   497.5 2166.18   503.8 2171.58   521.1 2183.35   561.2 2212.43   593.5 2233.09
#Mann= 6 ,-1,0
       0      .1       0  232.61     .05       0   233.5    .045       0
   259.1     .05       0  392.61     .06       0  422.61      .1       0
#XS Ineff= 2 , 0
           224.5  2137.8   268.1          2136.5
Permanent Ineff=
       F       F
Bank Sta=233.5,259.1
XS Rating Curve= 0 ,0
Exp/Cntr(USF)=0,0
Exp/Cntr=0.5,0.3

Type RM Length L Ch R = 1 ,113     ,79.5,79.5,79.5
BEGIN DESCRIPTION:
structure xs 2; 5.4 ft between structure and xs
END DESCRIPTION:
XS GIS Cut Line= 3
2231062.07888314452716.2811694112230998.48242657452821.109327576
2230703.10396047453187.791881335
#Sta/Elev= 30
       0 2228.83    80.6 2193.15   113.3 2180.62     139 2169.02   145.4 2165.54
   152.7 2157.27   158.4 2151.83   172.7 2142.88   177.3 2141.57   215.6 2141.59
   218.2  2140.9  226.872135.366   235.7 2134.09   250.3 2134.91   252.3 2136.14
   256.2 2140.23   261.4 2141.57   287.1 2139.14   329.1  2139.5     375 2138.75
   394.1  2139.8   410.3 2138.95   437.2  2139.4   457.1 2141.95   462.8 2144.37
   485.6 2159.78   538.7 2198.62   553.5 2208.73   572.6 2220.88   593.5 2232.31
#Mann= 6 ,-1,0
       0      .1       0  202.61     .05       0  226.87    .045       0
   250.3     .05       0  352.61     .06       0  442.61      .1       0
#XS Ineff= 3 ,-1
       0     225  2137.3     252  370.48  2136.5  370.48  532.39 2147.25
Permanent Ineff=
       F       F       F
Bank Sta=226.87,250.3
XS Rating Curve= 0 ,0
Exp/Cntr(USF)=0,0
Exp/Cntr=0.5,0.3

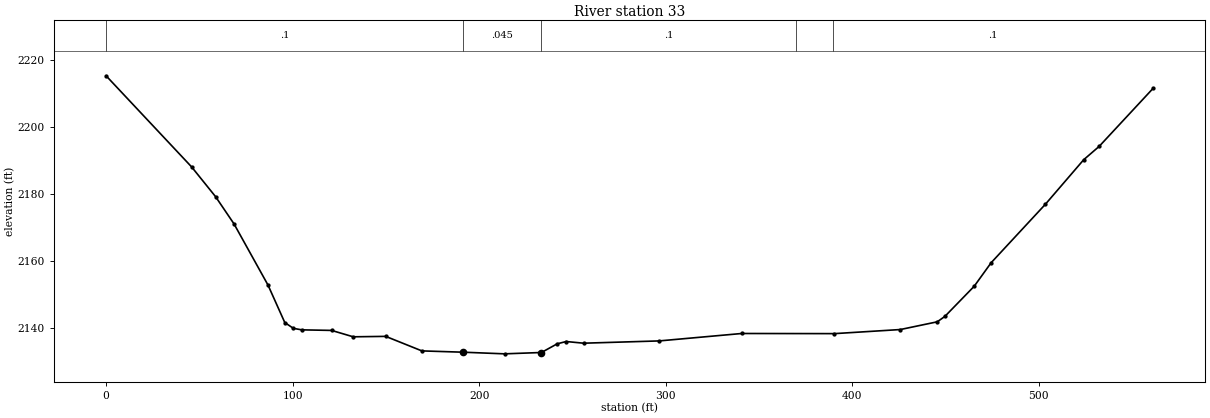
Type RM Length L Ch R = 1 ,33      ,,,
BEGIN DESCRIPTION:
structure xs 1
END DESCRIPTION:
XS GIS Cut Line= 4
2231040.54018492452726.0587937022230943.80734071452778.210414057
2230712.48966978 453020.463102162230683.04923894 453133.17789454
#Sta/Elev= 30
       0 2215.25    45.9 2187.99    58.7 2179.13    68.6 2170.98    86.8 2152.72
    95.8 2141.52   100.4 2139.78   104.9 2139.33   120.9 2139.16   132.5 2137.25
   149.9 2137.38   169.3 2133.04   191.4 2132.65   213.6 2132.16   233.4 2132.56
   241.9 2135.17   246.7 2135.84     256 2135.34   296.5 2136.02   340.8 2138.24
   390.5  2138.2   425.8 2139.42   445.6 2141.73   449.7 2143.35   465.4 2152.35
   474.5 2159.39   503.5 2176.81   524.1 2190.16   532.4 2194.15   561.3 2211.48
#Mann= 5 ,-1,0
       0      .1       0   191.4    .045       0   233.4      .1       0
   369.9     .06       0   389.9      .1       0
Bank Sta=191.4,233.4
XS Rating Curve= 0 ,0
Exp/Cntr(USF)=0,0
Exp/Cntr=0.3,0.1
LCMann Table=0

Chan Stop Cuts=-1
Use User Specified Reach Order=0
Composite Channel Slope=5